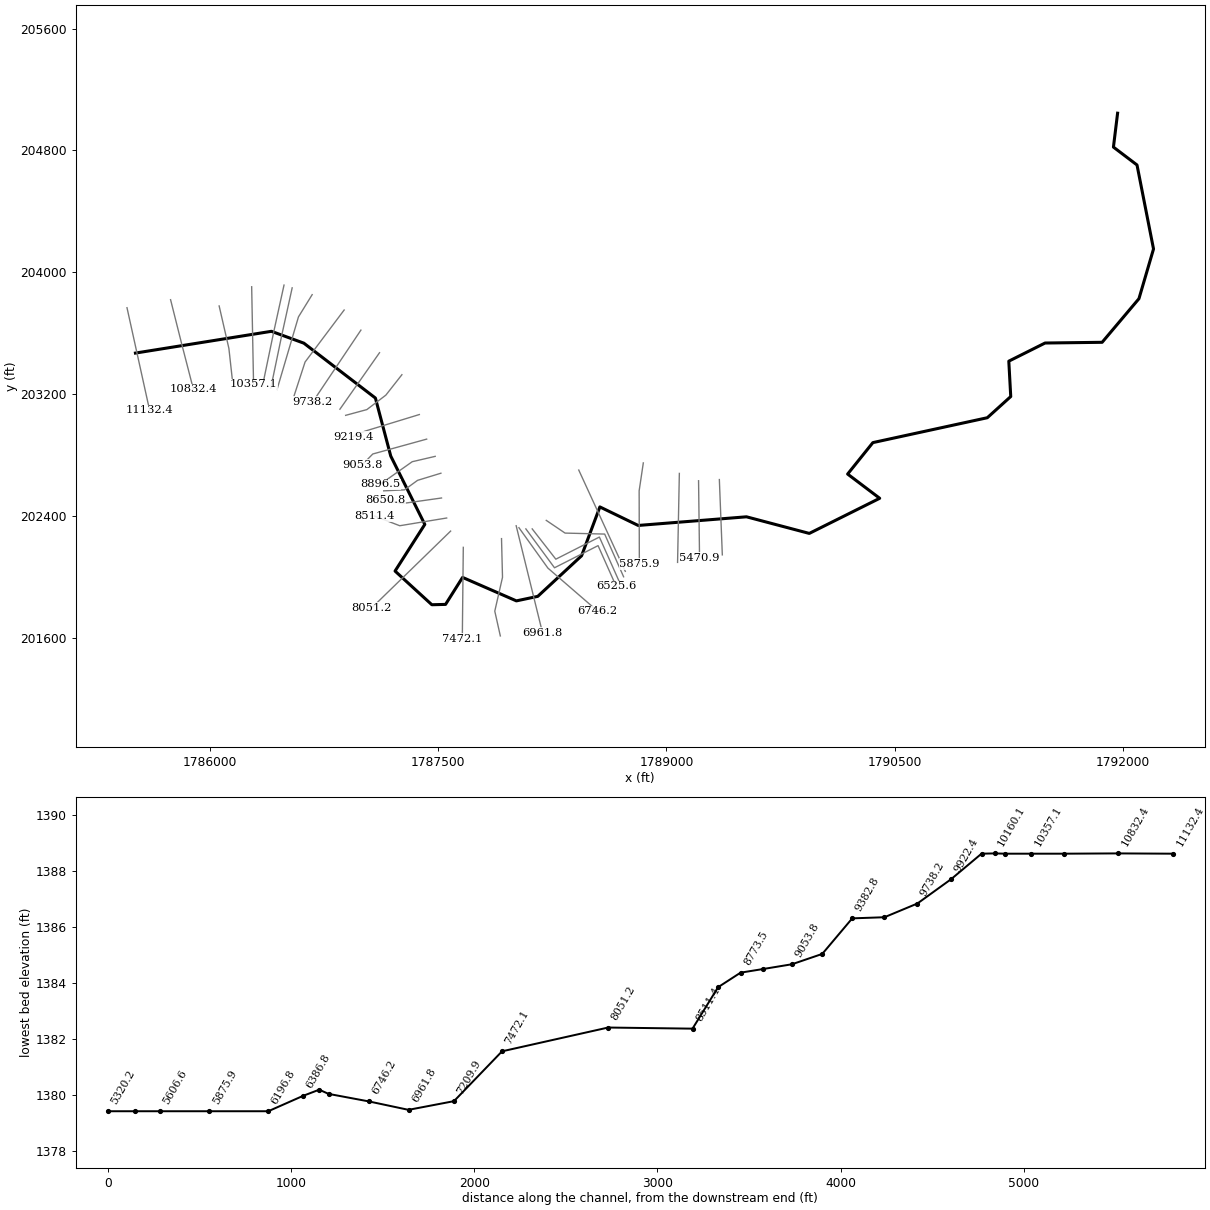
--- PECKSRN.prj (project) ---

Proj Title=PECKSRN
Current Plan=p01
Default Exp/Contr=0,0
English Units
Geom File=g01
Flow File=f01
Plan File=p01
BEGIN DESCRIPTION:
END DESCRIPTION:
DSS Export Rating Curves= 0
DSS Export Rating Curve Sorted= 0
DSS Export Volume Flow Curves= 0
DXF OffsetX= 0
DXF OffsetY= 0
DXF ScaleX= 0
DXF ScaleY= 0

--- PECKSRN.p01 (plan) ---

Plan Title=Floodplain
Program Version=4.00
Geom File=g01
Flow File=f01
K Sum by GR=0
Std Step Tol=0.01
Critical Tol=0.01
Num of Std Step Trials=20
Max Error Tol=0.3
Flow Tol Ratio=0.001
Split Flow NTrial=30
Split Flow Tol=0.02
Split Flow Ratio=0.02
Log Output Level=0
Friction Slope Method=1
Unsteady Friction Slope Method=2
Unsteady Bridges Friction Slope Method=1
Global Log Level=0
CheckData=False
Run HTab=0
Run UNet=0
Run PostProcess=0
UNET Theta=0
UNET Theta Warmup=0
UNET ZTol=0
UNET ZSATol=0
UNET MxIter=0
UNET MaxInSteps=0
UNET DtIC=0
UNET DtMin=0
UNET MaxCRTS=0
UNET WFStab=0
UNET SFStab=0
UNET WFX=0
UNET SFX=0
UNET DSS MLevel=0
UNET DZMax Abort=0
UNET Convert EG Bridges=0
UNET Use Existing IB Tables=0
UNET Froude Limit=0
UNET Froude Power=0
Write IC File=0
Echo Input=False
Echo Output=False
Write Detailed=0

--- PECKSRN.f01 (steady flow) ---

Flow Title=NFF Regression Equation
Program Version=5.03
Number of Profiles= 1
Profile Names=P100yr
River Rch & RM=PECKSRN,Main            ,11132.4
2218.484
River Rch & RM=PECKSRN,Main            ,583.6
2388.545
River Rch & RM=PECKSRN,Main            ,166
2389.124
Boundary for River Rch & Prof#=PECKSRN,Main            , 1
Up Type= 0
Dn Type= 3
Dn Slope=0.00375
DSS Import GetInterval= 0
DSS Import GetPeak= 0
DSS Import FillOption= 0

--- PECKSRN.g01 (geometry) ---

Geom Title=USGS 10m DEM
Program Version=4.10

River Reach=PECKSRN         ,Main
Reach XY= 30
     1785508.645      203468.554     1786402.655      203611.514
     1786616.001      203533.663     1787086.548      203173.088
     1787187.273      202792.055     1787411.293      202343.004
     1787215.586       202036.45     1787457.551      201815.274
     1787547.627      201817.523     1787659.586      201994.826
     1788013.383      201840.629     1788154.002      201870.339
     1788442.024      202136.952     1788562.378      202457.889
      1788814.34      202336.115     1789526.265      202392.946
     1789939.233      202283.828     1790402.142      202514.558
     1790191.328      202673.763     1790357.378       202880.37
     1791109.758      203043.839     1791263.814      203182.975
     1791251.099      203415.384     1791489.507      203534.625
     1791864.732      203539.317     1792106.769      203825.872
     1792202.616      204152.406     1792094.065      204704.188
     1791939.053      204821.675     1791966.347      205044.419

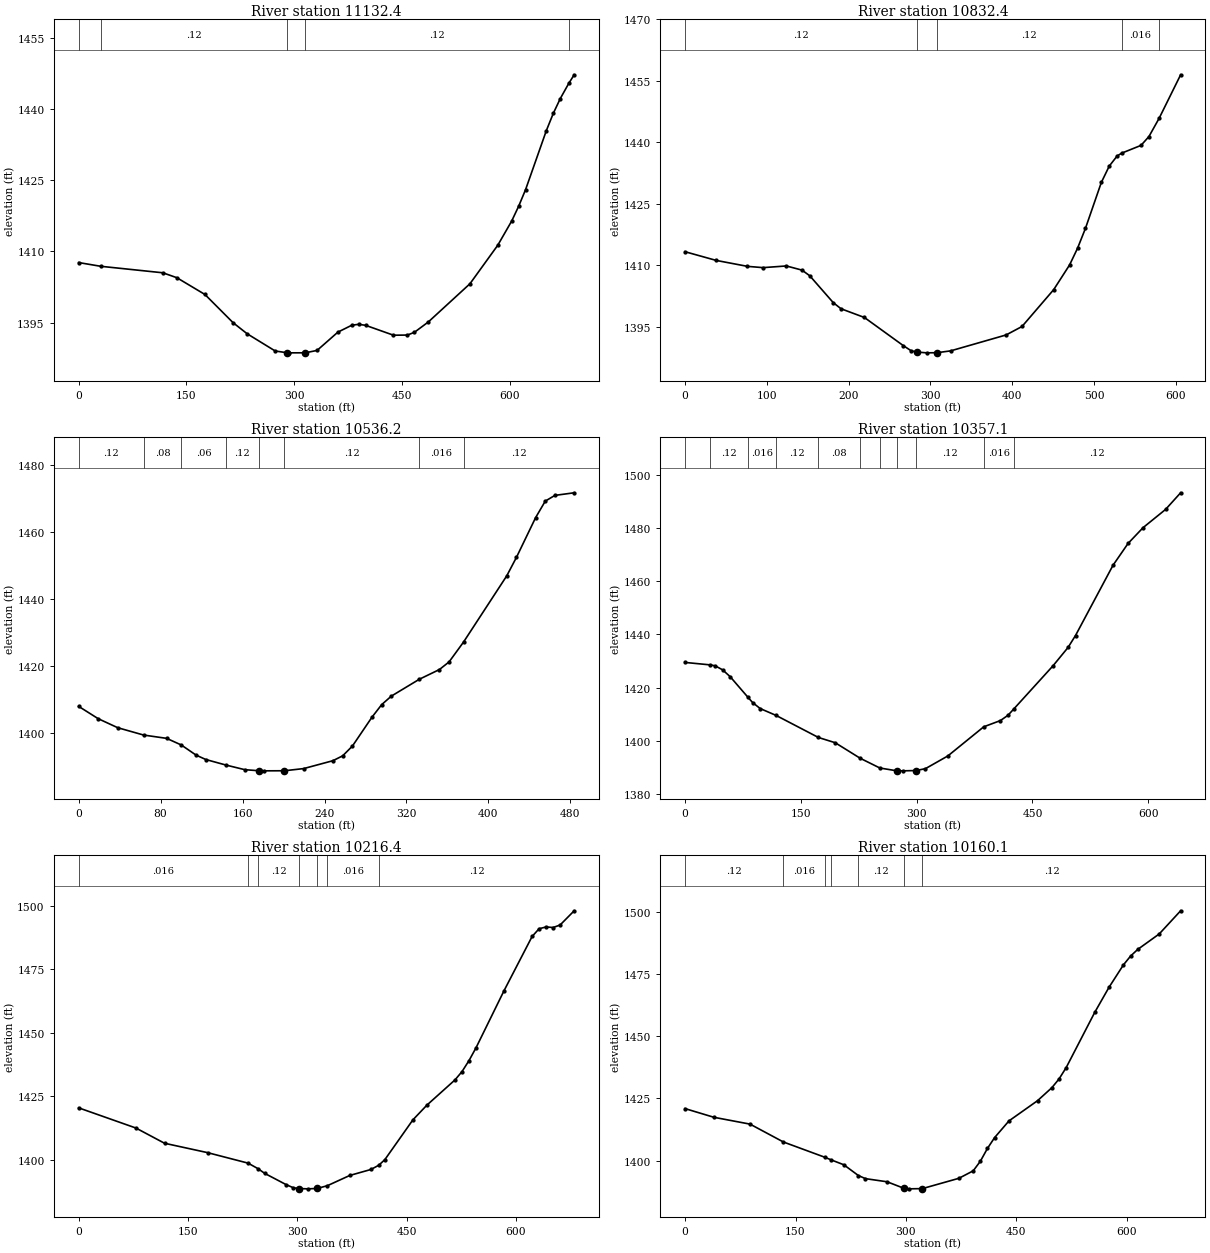
Type RM Length L Ch R = 1 ,11132.4 ,299.3,300,300.7
XS GIS Cut Line= 3
     1785453.107      203766.566      1785518.41       203470.71
     1785601.836      203092.752
#Sta/Elev= 30
       0 1407.66   30.771406.871   117.3  1405.5   136.8 1404.46   175.9 1400.92
     215 1394.98   234.6 1392.64   273.7    1389   290.51388.624   293.2 1388.61
   315.51388.616     332 1389.12     361 1392.98   380.4 1394.44   390.1 1394.63
   399.7 1394.41   438.4 1392.33   457.8 1392.36   467.5 1392.94   486.8 1395.11
   544.9 1403.19   583.6 1411.31     603 1416.42   612.6 1419.51   622.3 1423.03
   651.3 1435.52     661 1439.16   670.7 1442.27  682.411445.446     690 1447.28
#Mann= 5 ,-1 , 0
       0     .06       0   30.77     .12       0   290.5    .045       0
   315.5     .12       0  682.41    .016       0
Bank Sta=290.5,315.5
XS Rating Curve= 0 ,0
Exp/Cntr=0.3,0.1

Type RM Length L Ch R = 1 ,10832.4 ,296.6,296.2,295.6
XS GIS Cut Line= 3
     1785739.673      203819.253      1785811.76      203532.626
     1785889.405      203232.015
#Sta/Elev= 30
       0  1413.3    38.1 1411.18    76.3 1409.73    95.3 1409.42   123.9 1409.83
     143 1408.81   152.5 1407.42   181.2 1400.87   190.7 1399.38   219.3 1397.25
     267 1390.36   276.5 1389.12   283.11388.814   295.6 1388.62   308.11388.653
   324.7  1389.1   392.6 1392.99     412 1395.05   450.8 1404.06   470.2 1410.08
   479.9 1414.14   489.6 1419.01     509 1430.21   518.7 1434.21   528.4 1436.69
  533.881437.368   557.5 1439.26   567.2 1441.41  579.681445.873     606  1456.5
#Mann= 5 ,-1 , 0
       0     .12       0   283.1    .045       0   308.1     .12       0
  533.88    .016       0  579.68     .12       0
Bank Sta=283.1,308.1
XS Rating Curve= 0 ,0
Exp/Cntr=0.3,0.1

Type RM Length L Ch R = 1 ,10536.2 ,183.6,179.1,174.3
XS GIS Cut Line= 3
     1786059.008      203778.259     1786123.103      203499.118
     1786144.794      203303.024
#Sta/Elev= 30
       0 1407.89    19.1  1404.2    38.2  1401.5   63.461399.309    85.9 1398.32
  100.181396.344   114.6 1393.32   124.1    1392  143.79 1390.34   162.3 1388.95
   175.91388.643   180.9 1388.61   200.91388.636   219.6 1389.28   248.2 1391.64
   257.8 1393.11   267.3 1396.04   286.4 1404.68   295.8  1408.4   305.2 1410.94
  332.541415.989   352.2  1418.9   361.6 1421.18  375.71 1427.11   417.9 1446.91
   427.3  1452.4   446.1 1464.33   455.5 1469.25   464.9 1470.96   483.7 1471.74
#Mann= 8 ,-1 , 0
       0     .12       0   63.46     .08       0  100.18     .06       0
  143.79     .12       0   175.9    .045       0   200.9     .12       0
  332.54    .016       0  375.71     .12       0
Bank Sta=175.9,200.9
XS Rating Curve= 0 ,0
Exp/Cntr=0.3,0.1

Type RM Length L Ch R = 1 ,10357.1 ,146,140.7,135.7
XS GIS Cut Line= 2
     1786272.866      203904.157      1786285.32      203262.302
#Sta/Elev= 30
       0 1429.46   32.081428.549    38.9 1428.19    48.6 1426.67    58.4 1424.09
   80.851416.524    87.5 1414.33    97.3 1412.08  117.831409.499  172.691401.188
   194.5  1399.2  226.821393.353  252.331389.675     2741388.635   282.1 1388.61
     299 1388.72   311.3 1389.42   340.4 1394.22  386.961405.212   408.5 1407.55
   418.3 1409.54  425.531411.821   476.6 1428.17   496.1 1435.09   505.8  1439.6
   554.4 1466.08   573.9  1474.3   593.3 1480.24   622.5 1487.12     642 1493.39
#Mann= 11 ,-1 , 0
       0     .06       0   32.08     .12       0   80.85    .016       0
  117.83     .12       0  172.69     .08       0  226.82     .06       0
  252.33     .12       0     274    .045       0     299     .12       0
  386.96    .016       0  425.53     .12       0
Bank Sta=274,299
XS Rating Curve= 0 ,0
Exp/Cntr=0.3,0.1

Type RM Length L Ch R = 1 ,10216.4 ,56.3,56.3,56.2
XS GIS Cut Line= 3
     1786485.528      203915.246      1786417.99      203608.092
     1786343.544      203250.151
#Sta/Elev= 30
       0 1420.51    78.6 1412.56   117.9 1406.56   176.9 1402.87   232.51398.737
  246.191396.552   255.5 1394.68     285 1390.24   294.8 1389.02   302.31388.717
   314.5 1388.61   327.31388.753  341.391389.848   372.2 1393.89   401.1 1396.23
  411.891397.895   420.3 1400.12   458.8 1415.79     478 1421.58   516.5  1431.5
   526.2  1434.8   535.8 1439.13   545.4 1444.16   583.9 1466.67   622.4 1488.01
     632 1491.05   641.6 1491.74   651.2 1491.52   660.8 1492.51   680.1 1498.11
#Mann= 7 ,-1 , 0
       0    .016       0   232.5     .08       0  246.19     .12       0
   302.3    .045       0   327.3     .12       0  341.39    .016       0
  411.89     .12       0
Bank Sta=302.3,327.3
XS Rating Curve= 0 ,0
Exp/Cntr=0.3,0.1

Type RM Length L Ch R = 1 ,10160.1 ,73.4,71.9,70
XS GIS Cut Line= 3
      1786539.16      203897.031     1786471.809      203590.731
     1786398.586      203238.664
#Sta/Elev= 30
       0 1420.87    39.2 1417.38    88.2 1414.64  133.611407.447  189.491401.354
  198.381400.268   215.6  1398.3  235.35 1393.98     245 1392.72   274.4 1391.46
   297.31388.839   303.8 1388.62   322.3 1388.71   371.9 1392.85   391.4 1395.86
   401.1 1399.71   410.8  1404.9   420.5 1409.23     440 1415.94   478.8 1424.06
   498.3  1429.3     508 1432.79   517.7 1437.36   556.6 1459.62     576  1469.7
   595.5 1478.67   605.2  1482.2   614.9 1484.88   644.1 1491.09   673.2 1500.41
#Mann= 7 ,-1 , 0
       0     .12       0  133.61    .016       0  189.49     .06       0
  198.38     .08       0  235.35     .12       0   297.3    .045       0
   322.3     .12       0
Bank Sta=297.3,322.3
XS Rating Curve= 0 ,0
Exp/Cntr=0.3,0.1

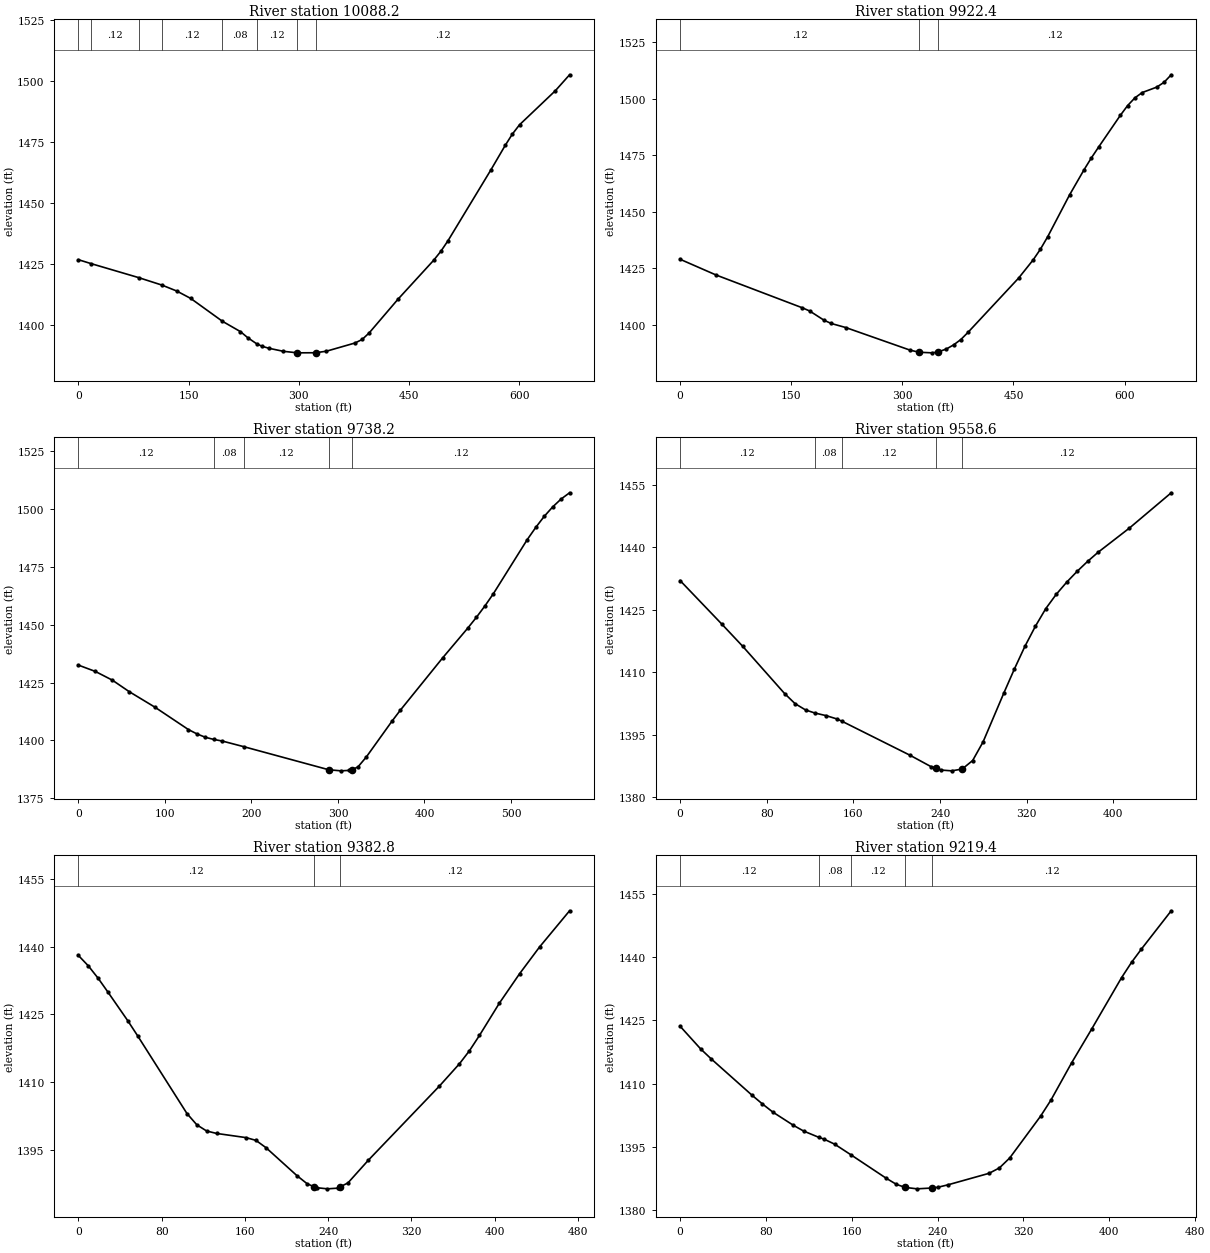
Type RM Length L Ch R = 1 ,10088.2 ,173.9,165.8,157.7
XS GIS Cut Line= 3
     1786670.662       203852.37     1786580.434       203706.12
      1786439.87      203230.048
#Sta/Elev= 30
       0 1426.73   17.371425.114    81.81419.414  113.641416.339   133.7 1413.92
   152.8 1410.88  195.871401.533   220.5 1397.28   230.2 1394.85  242.281392.358
   249.7 1391.31   259.4 1390.46   278.9 1389.23   297.61388.625   298.4 1388.61
   322.6 1388.65   337.3 1389.27   376.2 1392.63     386 1394.08   395.7 1396.81
   434.6  1410.5   483.3  1426.5     493 1430.14   502.8  1434.5   561.2 1463.52
   580.6  1473.5   590.4 1478.16   600.1 1481.95   648.8 1495.88   668.2 1502.42
#Mann= 8 ,-1 , 0
       0     .06       0   17.37     .12       0    81.8     .06       0
  113.64     .12       0  195.87     .08       0  242.28     .12       0
   297.6    .045       0   322.6     .12       0
Bank Sta=297.6,322.6
XS Rating Curve= 0 ,0
Exp/Cntr=0.3,0.1

Type RM Length L Ch R = 1 ,9922.4  ,182.9,184.2,185.4
XS GIS Cut Line= 3
     1786880.935      203751.461      1786623.96      203409.795
     1786551.044      203185.836
#Sta/Elev= 30
       0 1429.03    48.6 1422.08   165.2 1407.57   174.9 1406.19   194.3 1402.11
     204 1400.67   223.5 1398.89   310.9 1388.84     3231387.959   340.1  1387.7
     3481388.065   359.5  1389.4   369.2 1391.21   378.9 1393.54   388.6 1396.72
     457 1420.72   476.6 1428.75   486.4 1433.46   496.2 1438.96   525.7 1457.42
   545.3 1468.56   555.1 1473.75   564.9 1478.55   594.4 1492.64   604.2 1496.94
     614 1500.33   623.8 1502.66   643.4 1505.05   653.2 1507.16     663 1510.51
#Mann= 3 ,-1 , 0
       0     .12       0     323    .045       0     348     .12       0
Bank Sta=323,348
XS Rating Curve= 0 ,0
Exp/Cntr=0.3,0.1

Type RM Length L Ch R = 1 ,9738.2  ,180.1,179.6,179.1
XS GIS Cut Line= 2
     1786991.148       203619.43     1786674.741      203148.076
#Sta/Elev= 30
       0 1432.54    19.6  1429.8    39.2 1426.04    58.7 1421.07    88.1 1414.43
   127.2 1404.66     137  1402.8   146.8 1401.33  156.211400.427   166.4  1399.7
  191.39 1397.25  289.32  1387.3   303.4 1386.83   313.2 1387.03  316.06 1387.36
     323 1388.48   332.8 1392.83   362.2 1408.18   371.9 1412.96   420.9 1435.63
   450.2 1448.62     460  1453.2   469.8  1458.1   479.6  1463.4   518.8 1486.82
   528.6 1492.07   538.3 1496.81   548.1 1500.91   557.9 1504.35   567.7 1507.05
#Mann= 5 ,-1 , 0
       0     .12       0  156.21     .08       0  191.39     .12       0
  289.32    .045       0  316.06     .12       0
Bank Sta=289.32,316.06
XS Rating Curve= 0 ,0
Exp/Cntr=0.3,0.1

Type RM Length L Ch R = 1 ,9558.6  ,182.8,175.8,168.8
XS GIS Cut Line= 2
     1787113.544      203470.992     1786853.127      203099.899
#Sta/Elev= 30
       0 1432.02    38.6 1421.54    57.9 1416.21    96.5 1404.89   106.1 1402.48
   115.8 1400.96  124.261400.229     135 1399.58   144.7  1398.8  149.651398.217
   212.2 1390.09   231.5 1387.37  236.32 1387.01   241.1 1386.52   250.8 1386.34
   260.4 1386.77   270.1 1388.82   279.7 1393.28     299 1405.09   308.7 1410.83
   318.3 1416.21     328 1421.04   337.6 1425.28   347.2 1428.69   356.9 1431.62
   366.5 1434.21   376.2 1436.61   385.8 1438.78   414.8 1444.61   453.4 1453.08
#Mann= 5 ,-1 , 0
       0     .12       0  124.26     .08       0  149.65     .12       0
  236.32    .045       0   260.4     .12       0
Bank Sta=236.32,260.4
XS Rating Curve= 0 ,0
Exp/Cntr=0.3,0.1

Type RM Length L Ch R = 1 ,9382.8  ,171.4,163.5,155.5
XS GIS Cut Line= 4
     1787260.679      203326.461      1787155.21      203192.347
      1787030.21      203097.295     1786890.887      203059.534
#Sta/Elev= 30
       0  1438.1     9.5  1435.8      19 1433.03    28.4 1429.96    47.4 1423.63
    56.9 1420.27   104.3 1403.02   113.8 1400.51   123.2 1399.14   132.7  1398.6
   161.1 1397.67   170.6 1397.06   180.4 1395.41   209.9 1389.25   219.7 1387.45
  226.21 1386.78   229.5 1386.54   239.3  1386.3   249.1 1386.45   251.1  1386.7
     259 1387.61   278.6 1392.65   346.9 1409.11   366.2 1414.07   375.8 1416.96
   385.4 1420.35   404.6 1427.54   423.9 1434.03   443.1 1439.97     472 1448.02
#Mann= 3 ,-1 , 0
       0     .12       0  226.21    .045       0   251.1     .12       0
Bank Sta=226.21,251.1
XS Rating Curve= 0 ,0
Exp/Cntr=0.3,0.1

Type RM Length L Ch R = 1 ,9219.4  ,166.2,165.6,165
XS GIS Cut Line= 3
     1787375.262      203064.742     1787017.189      202955.367
     1786941.669      202920.211
#Sta/Elev= 30
       0 1423.64    19.2 1418.24    28.8 1415.93    67.2 1407.22    76.8 1405.17
    86.4 1403.26   105.6 1400.11   115.2 1398.74  129.051397.285   134.4  1396.8
     144 1395.64  159.631393.041     192 1387.56   201.6 1386.09   209.81385.372
   220.8 1385.03   234.81385.228     240 1385.39   249.6 1385.98     288 1388.72
   297.6    1390   307.2 1392.36     336  1402.3   345.6  1406.1   364.8 1414.91
   383.7 1423.02   411.4 1435.16   420.7 1438.79   429.9 1441.95   457.7 1451.04
#Mann= 5 ,-1 , 0
       0     .12       0  129.05     .08       0  159.63     .12       0
   209.8    .045       0   234.8     .12       0
Bank Sta=209.8,234.8
XS Rating Curve= 0 ,0
Exp/Cntr=0.3,0.1

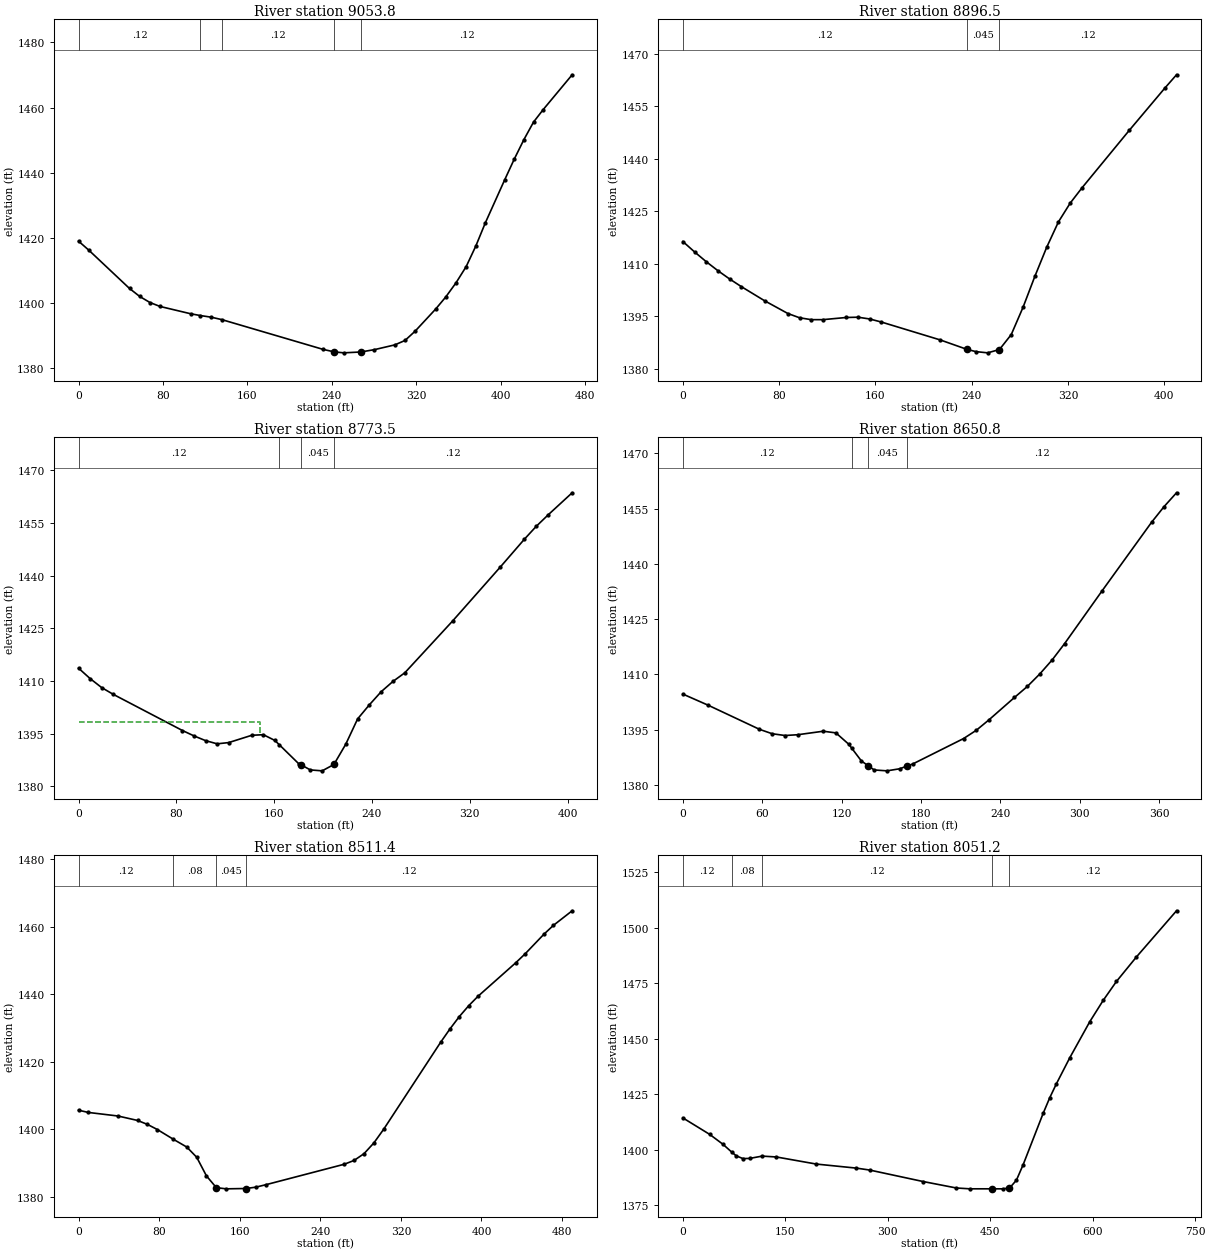
Type RM Length L Ch R = 1 ,9053.8  ,149.5,157.3,165
XS GIS Cut Line= 3
     1787423.439      202903.284     1787069.273      202805.628
      1786998.96      202734.013
#Sta/Elev= 30
       0 1418.96     9.7  1416.2    48.3 1404.43      58 1401.97    67.7 1400.11
    77.3  1398.9   106.4 1396.65  115.461396.112   125.7 1395.61  135.761394.865
     232  1385.7   242.51384.944   251.4 1384.66   267.51384.921   280.4 1385.64
   299.7  1387.1   309.4 1388.46     319 1391.32   338.4 1398.09     348 1401.81
   357.7 1406.15   367.4 1411.17   376.5 1417.46   385.6 1424.64   403.9 1437.82
     413  1444.2   422.1 1450.16   431.2 1455.53   440.4 1459.38   467.8 1470.05
#Mann= 5 ,-1 , 0
       0     .12       0  115.46     .08       0  135.76     .12       0
   242.5    .045       0   267.5     .12       0
Bank Sta=242.5,267.5
XS Rating Curve= 0 ,0
Exp/Cntr=0.3,0.1

Type RM Length L Ch R = 1 ,8896.5  ,122.6,123,123.3
XS GIS Cut Line= 3
     1787479.429      202790.003     1787328.387      202754.847
     1787120.054      202607.711
#Sta/Elev= 30
       0 1416.32     9.7 1413.35    19.4 1410.56    29.1 1407.98    38.8 1405.62
    48.5 1403.44    67.8  1399.4    87.2 1395.74    96.9 1394.52   106.6 1393.98
   116.3 1393.98   135.7  1394.6   145.4 1394.68   155.1 1394.18   164.9  1393.3
   213.9 1388.17   235.8 1385.51   243.4 1384.84   253.2 1384.49     263 1385.44
   272.8 1389.71   282.6 1397.52   292.4 1406.35   302.2 1414.64     312 1421.94
   321.8 1427.32   331.6 1431.69   370.9 1448.14   400.3 1460.16   410.1 1464.01
#Mann= 3 ,-1 , 0
       0     .12       0   235.8    .045       0     263     .12       0
Bank Sta=235.8,263
XS Rating Curve= 0 ,0
Exp/Cntr=0.3,0.1

Type RM Length L Ch R = 1 ,8773.5  ,133.8,122.7,111.7
XS GIS Cut Line= 4
     1787517.189      202679.326     1787363.544      202632.451
     1787277.606      202569.951     1787140.887       202563.44
#Sta/Elev= 30
       0 1413.62     9.4 1410.67    18.9 1408.09    28.4 1406.16      85 1395.85
    94.5 1394.31   103.9 1392.97   113.4 1392.06   122.8 1392.41   141.7 1394.49
   151.2 1394.66   160.6 1393.02  164.311391.773     180 1386.43  182.27 1386.04
   189.6 1384.62   199.3 1384.36   208.9 1386.17   218.6 1391.95   228.3 1399.16
   237.9 1403.17   247.6 1406.92   257.2 1409.84   266.9  1412.3     306 1427.06
   345.1 1442.47   364.7 1450.36   374.4 1454.03   384.2 1457.32   403.8  1463.6
#Mann= 4 ,-1 , 0
       0     .12       0  164.31     .08       0  182.27    .045       0
   208.9     .12       0
#XS Ineff= 2 , 0
          148.09 1398.24
Permanent Ineff=
       F       F
Bank Sta=182.27,208.9
XS Rating Curve= 0 ,0
Exp/Cntr=0.3,0.1

Type RM Length L Ch R = 1 ,8650.8  ,138.7,139.4,139.8
XS GIS Cut Line= 3
     1787521.096      202516.565     1787263.283      202480.107
     1787152.606      202502.242
#Sta/Elev= 29
       0 1404.67    19.3 1401.62    57.9 1395.11    67.5 1393.91    77.2 1393.43
    86.8 1393.64   106.1 1394.59   115.7 1394.14   125.4 1391.06  127.661389.987
     135  1386.5  140.12 1385.22   144.6 1384.08   154.3 1383.84   163.9  1384.4
  169.25 1385.12   173.6 1385.67   212.2  1392.6   221.8 1394.84   231.4 1397.68
   250.7 1403.76   260.4 1406.74   269.8 1410.12   279.2 1413.95   288.6 1418.38
   316.8 1432.63   354.4 1451.33   363.8 1455.56   373.2 1459.31
#Mann= 4 ,-1 , 0
       0     .12       0  127.66     .08       0  140.12    .045       0
  169.25     .12       0
Bank Sta=140.12,169.25
XS Rating Curve= 0 ,0
Exp/Cntr=0.3,0.1

Type RM Length L Ch R = 1 ,8511.4  ,446.3,460.3,474.2
XS GIS Cut Line= 3
      1787554.95      202385.055     1787246.356      202334.274
     1787080.991      202398.076
#Sta/Elev= 30
       0 1405.63     9.8 1404.97    39.1 1403.92    58.6  1402.6    68.4 1401.43
    78.2 1399.92   94.041397.045   107.5 1394.72   117.3 1391.71     127 1386.18
   136.8 1382.71   146.6 1382.36   166.2 1382.46   175.9 1382.85   185.7 1383.56
   263.9 1389.65   273.6 1390.78   283.4 1392.77   293.2 1395.96     303 1400.04
   359.4 1425.72   368.7 1429.69     378 1433.35   387.4 1436.59   396.7  1439.4
     434 1449.27   443.4 1451.94     462 1457.73   471.3 1460.32     490 1464.66
#Mann= 4 ,-1 , 0
       0     .12       0   94.04     .08       0   136.8    .045       0
   166.2     .12       0
Bank Sta=136.8,166.2
XS Rating Curve= 0 ,0
Exp/Cntr=0.3,0.1

Type RM Length L Ch R = 1 ,8051.2  ,560.5,579.1,596.6
XS GIS Cut Line= 2
     1787580.991      202299.117     1787062.762      201795.211
#Sta/Elev= 30
       0 1414.32    39.1 1406.94    58.6 1402.48   71.641398.898    78.1 1397.26
    87.9 1396.02    97.7 1396.09     1161397.129   136.8 1396.75   195.4 1393.55
     254 1391.73   273.5 1390.86   351.6  1385.7   400.5 1382.78     420 1382.41
   452.6 1382.41   468.9  1382.4   477.61382.795   478.6 1382.84   488.4 1386.31
   498.2 1393.24   527.5 1416.36   537.2 1423.43     547 1429.74   566.5  1441.4
   595.8 1457.64   615.4 1467.22   634.9 1475.78   664.2 1486.82   722.8 1507.57
#Mann= 5 ,-1 , 0
       0     .12       0   71.64     .08       0     116     .12       0
   452.6    .045       0   477.6     .12       0
Bank Sta=452.6,477.6
XS Rating Curve= 0 ,0
Exp/Cntr=0.3,0.1

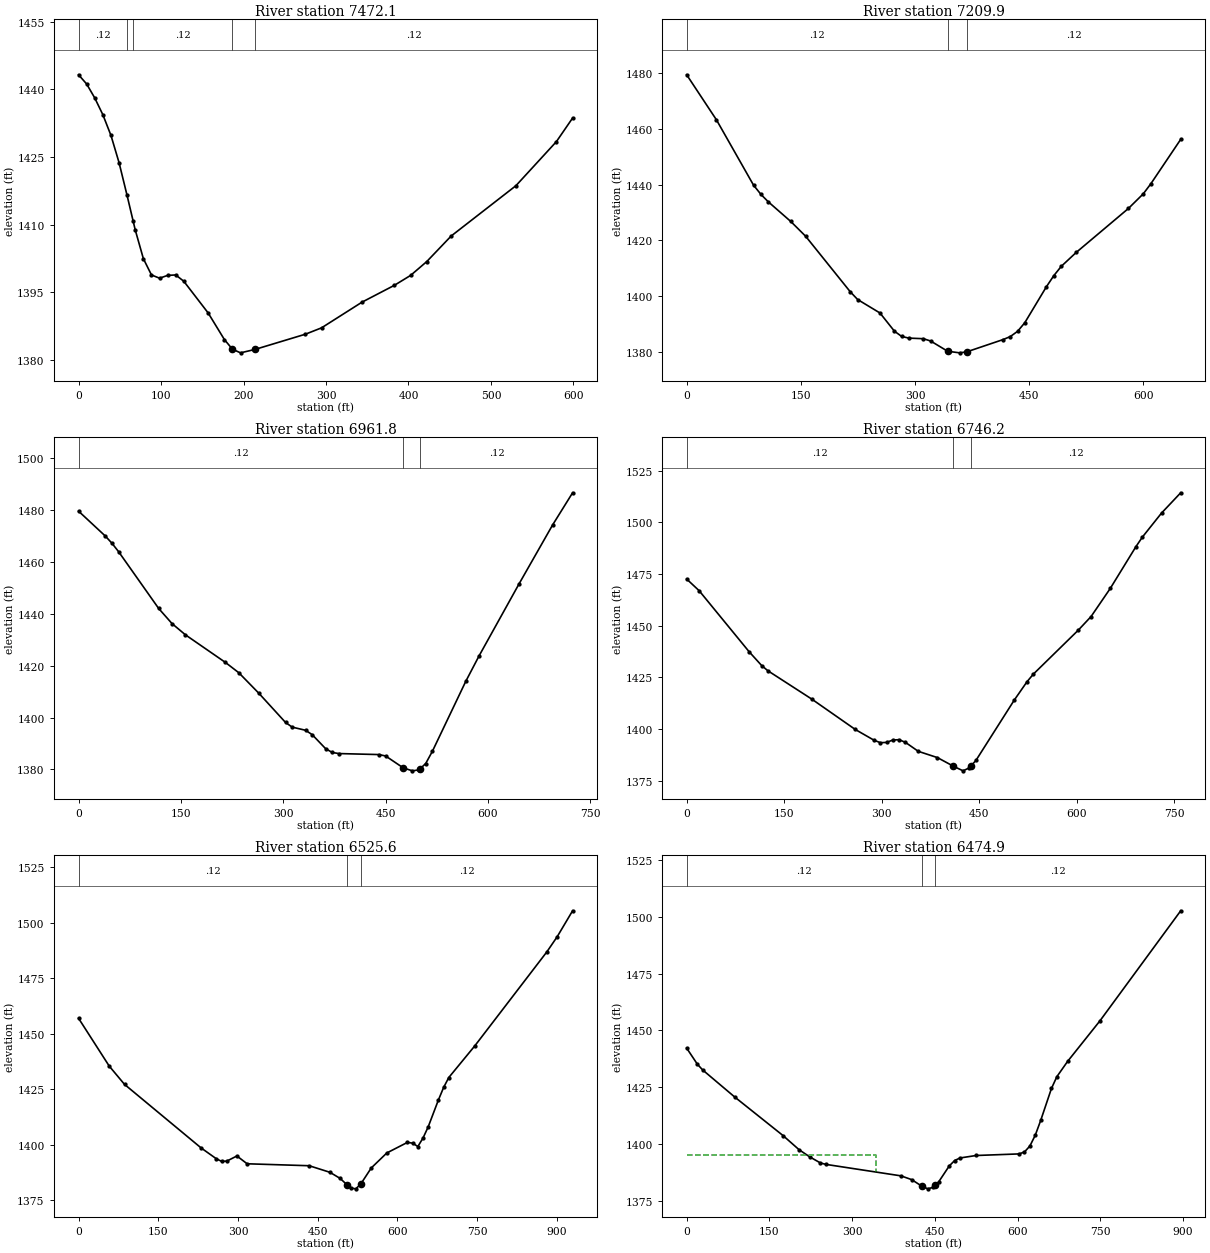
Type RM Length L Ch R = 1 ,7472.1  ,267.1,262.2,257.7
XS GIS Cut Line= 2
     1787664.325      202192.347     1787657.814      201593.388
#Sta/Elev= 30
       0  1443.2     9.8 1441.16    19.6 1438.07    29.5 1434.33    39.3 1429.75
    49.1 1423.72   58.631416.602   66.061410.862    68.7 1408.82    78.6 1402.42
    88.4 1398.82    98.2  1398.1     108 1398.72   117.8 1398.82   127.6 1397.42
   157.1  1390.4   176.8  1384.5   186.6 1382.35   196.4 1381.55  213.81  1382.3
     275 1385.68   294.6 1387.09   343.7 1392.79     383 1396.53   402.6 1398.72
   422.2 1401.79   451.7 1407.44   530.3 1418.61   579.4 1428.39     599 1433.61
#Mann= 5 ,-1 , 0
       0     .12       0   58.63     .08       0   66.06     .12       0
   186.6    .045       0  213.81     .12       0
Bank Sta=186.6,213.81
XS Rating Curve= 0 ,0
Exp/Cntr=0.3,0.1

Type RM Length L Ch R = 1 ,7209.9  ,237.4,248.1,258.4
XS GIS Cut Line= 4
     1787915.627      202249.638     1787922.137      201995.732
     1787871.356      201773.076     1787907.814      201610.315
#Sta/Elev= 30
       0 1479.27    39.1 1463.16    87.9 1439.76    97.7 1436.43   107.5 1433.75
   136.8 1426.78   156.3  1421.5   214.9 1401.64   224.7 1398.84     254 1394.03
     273 1387.52   282.5 1385.64     292 1385.04   311.1 1384.83   320.6    1384
     3431380.333   358.7 1379.77     3681380.122   415.8 1384.52   425.3  1385.6
   434.8 1387.46   444.3 1390.54   472.8 1403.46   482.4 1407.37   492.2 1410.71
   511.8 1415.68   580.5 1431.44   600.1  1436.7   609.9 1440.25   649.2 1456.16
#Mann= 3 ,-1 , 0
       0     .12       0     343    .045       0     368     .12       0
Bank Sta=343,368
XS Rating Curve= 0 ,0
Exp/Cntr=0.3,0.1

Type RM Length L Ch R = 1 ,6961.8  ,201.2,215.7,229.3
XS GIS Cut Line= 2
     1788011.981      202334.274     1788185.158      201631.149
#Sta/Elev= 30
       0 1479.57    39.1    1470    48.9 1467.21    58.7 1463.94   117.4 1442.06
     137 1436.22   156.6  1431.9   215.3 1421.24   234.9 1417.27   264.2 1409.38
   303.4  1398.1   313.1 1396.31   332.7  1395.1   342.5 1393.39   362.1 1388.01
   371.8 1386.54   381.6 1386.12   440.4 1385.73   450.1 1385.18  475.97 1380.59
   489.3 1379.46   499.1 1379.83     501 1380.36   508.8 1382.28   518.6    1387
   567.6    1414   587.1 1423.82   645.8 1451.62   694.8 1474.25   724.1 1486.65
#Mann= 3 ,-1 , 0
       0     .12       0  475.97    .045       0     501     .12       0
Bank Sta=475.97,501
XS Rating Curve= 0 ,0
Exp/Cntr=0.3,0.1

Type RM Length L Ch R = 1 ,6746.2  ,167.8,220.6,248.7
XS GIS Cut Line= 3
      1788030.21      202321.253     1788220.625      202055.946
     1788548.356      201772.906
#Sta/Elev= 30
       0 1472.55    19.2  1466.9      96 1437.39   115.3  1430.7   124.9 1428.17
   192.1 1414.52   259.3 1399.76   288.2 1394.55   297.8 1393.38   307.4 1393.51
     317 1394.67   326.6 1394.83   336.4 1393.53   356.1  1389.2   385.6 1386.16
  410.16 1381.99     425 1379.76   434.8 1381.26   436.4  1381.9   444.7 1384.77
   503.7    1414   523.4 1422.92   533.2  1426.6   602.1 1447.81   621.8 1454.42
   651.3 1468.01   690.7  1488.2   700.6 1492.82   730.1 1504.46   759.6 1514.28
#Mann= 3 ,-1 , 0
       0     .12       0  410.16    .045       0   436.4     .12       0
Bank Sta=410.16,436.4
XS Rating Curve= 0 ,0
Exp/Cntr=0.3,0.1

Type RM Length L Ch R = 1 ,6525.6  ,74,50.7,54.4
XS GIS Cut Line= 4
     1788075.783       202313.44     1788264.028      202058.116
     1788550.487      202203.516     1788669.126      201937.504
#Sta/Elev= 30
       0 1456.93    57.7 1435.38    86.5 1427.13   230.7 1398.46   259.5 1393.56
   269.2 1392.42   278.8 1392.52     298 1394.85   317.2 1391.33     434 1390.45
     473 1387.49   492.4 1384.71   505.91381.687   511.9 1380.42   521.6 1380.03
   530.91382.136   550.8 1389.44   580.1 1396.21     619 1400.99   628.7 1400.62
   638.5 1399.11   648.2 1402.93   657.9 1407.94   677.3 1420.18     687 1425.75
   696.7 1430.22   745.3 1444.39   881.2 1486.87   900.6 1493.67   929.7 1505.41
#Mann= 3 ,-1 , 0
       0     .12       0   505.9    .045       0   530.9     .12       0
Bank Sta=505.9,530.9
XS Rating Curve= 0 ,0
Exp/Cntr=0.3,0.1

Type RM Length L Ch R = 1 ,6474.9  ,101.3,88.1,72.6
XS GIS Cut Line= 4
      1788117.45       202313.44     1788272.709       202114.54
     1788559.167      202259.939     1788690.474      201965.524
#Sta/Elev= 30
       0 1442.17    19.4 1435.09    29.1 1432.54    87.3  1420.6   174.7 1403.66
   203.8 1397.43   223.2 1394.26   242.6 1391.58   252.3 1390.96   388.6  1385.9
   408.1 1384.23   425.9 1381.44   437.3 1380.18     447 1380.87   450.91381.789
   456.8 1383.18   476.2 1390.28     486 1392.66   495.7 1393.78   524.9 1394.87
   602.9 1395.57   612.6 1396.44   622.4 1399.05   632.2 1403.84     642 1410.32
   661.5  1424.4   671.3 1429.59   690.8 1436.34   749.4 1454.19   895.9 1502.69
#Mann= 3 ,-1 , 0
       0     .12       0   425.9    .045       0   450.9     .12       0
#XS Ineff= 2 , 0
          343.65  1394.9
Permanent Ineff=
       F       F
Bank Sta=425.9,450.9
XS Rating Curve= 0 ,0
Exp/Cntr=0.3,0.1

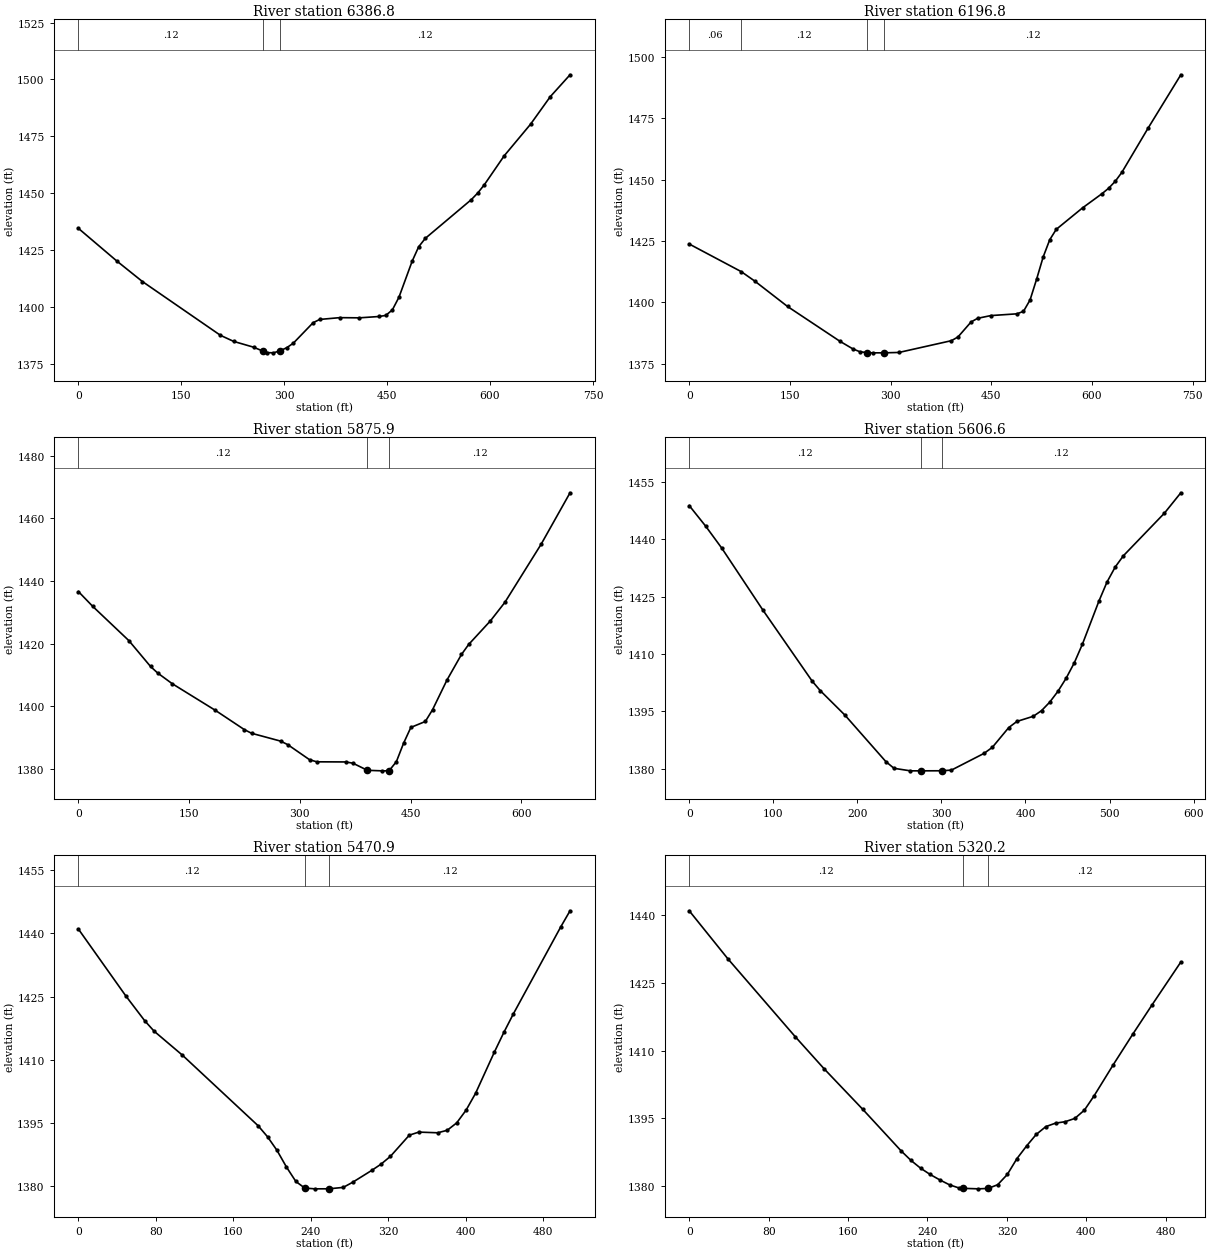
Type RM Length L Ch R = 1 ,6386.8  ,215.7,190,164.2
XS GIS Cut Line= 4
     1788209.898       202369.43     1788333.473      202285.981
     1788593.889       202279.47     1788718.365       201998.89
#Sta/Elev= 30
       0  1434.6    55.9 1420.29    93.2 1411.28     207 1387.65   226.3 1384.98
   255.2 1382.45   268.41380.782   274.5 1380.07   284.2 1379.96   293.41380.803
   303.5 1382.19   313.1 1384.16   342.1  1393.2   351.7 1394.62   380.7 1395.41
   409.6 1395.33   438.4 1395.92     448  1396.4   457.6 1398.81   467.2 1404.37
   486.4 1420.16   495.9  1426.5   505.5 1430.19   572.7 1447.23   582.3 1450.22
   591.9 1453.87   620.6 1466.47     659 1480.33   687.8 1492.44   716.6 1502.05
#Mann= 3 ,-1 , 0
       0     .12       0   268.4    .045       0   293.4     .12       0
Bank Sta=268.4,293.4
XS Rating Curve= 0 ,0
Exp/Cntr=0.3,0.1

Type RM Length L Ch R = 1 ,6196.8  ,330.6,321,311
XS GIS Cut Line= 2
     1788423.439      202700.159     1788729.429      202034.795
#Sta/Elev= 30
       0 1423.79   77.471412.532    97.6 1408.68   146.5 1398.31   224.6 1384.11
   244.1 1380.97   253.9  1379.9   265.51379.459   273.4 1379.41   290.5 1379.41
   312.5 1379.57   390.6 1384.37   400.4 1385.89   419.9    1392   429.6 1393.48
   449.2  1394.6   488.2 1395.32     498 1396.34   507.8 1400.99   517.5 1409.42
   527.3  1418.5   537.1 1425.54   546.8 1429.77   585.9 1438.51   615.2 1444.37
   624.9 1446.55   634.7 1449.37   644.5    1453   683.5    1471   732.4 1492.81
#Mann= 4 ,-1 , 0
       0     .06       0   77.47     .12       0   265.5    .045       0
   290.5     .12       0
Bank Sta=265.5,290.5
XS Rating Curve= 0 ,0
Exp/Cntr=0.3,0.1

Type RM Length L Ch R = 1 ,5875.9  ,269.6,269.3,268.5
XS GIS Cut Line= 3
     1788847.919      202747.034     1788820.575       202563.44
     1788821.877      202082.972
#Sta/Elev= 30
       0 1436.63    19.5 1431.88    68.4 1420.96    97.7 1412.72   107.5 1410.61
     127 1407.24   185.6 1398.71   224.8 1392.57   234.6  1391.4   273.9  1388.9
   283.7 1387.76   313.1 1382.97   322.9 1382.29   362.1 1382.25   371.9 1381.85
   391.5 1379.58   411.2 1379.41   420.8 1379.41   430.8 1382.34   440.6 1388.25
   450.4 1393.27     470 1395.16   479.8 1398.92   499.4 1408.42     519 1416.56
   528.8 1419.77   558.2 1427.28   577.8 1433.19   626.9 1451.74   666.1 1468.17
#Mann= 3 ,-1 , 0
       0     .12       0   391.5    .045       0   420.8     .12       0
Bank Sta=391.5,420.8
XS Rating Curve= 0 ,0
Exp/Cntr=0.3,0.1

Type RM Length L Ch R = 1 ,5606.6  ,134.9,135.7,136.5
XS GIS Cut Line= 2
     1789084.898      202678.024     1789073.179      202093.388
#Sta/Elev= 30
       0 1448.85    19.5 1443.48      39 1437.62    87.7 1421.47   146.2 1402.91
   155.9  1400.4   185.2    1394   233.9 1381.83   243.6 1380.07   263.1 1379.41
   275.4 1379.41   300.41379.427   311.9  1379.6   350.8 1383.99   360.6 1385.57
   380.1 1390.74   389.8 1392.34   409.3 1393.69   419.1 1395.17   428.8 1397.38
   438.6 1400.22   448.3 1403.63   458.1  1407.7   467.8 1412.61   487.3 1423.81
     497 1428.84   506.8 1432.79   516.5 1435.72   565.3 1446.87   584.8  1452.2
#Mann= 3 ,-1 , 0
       0     .12       0   275.4    .045       0   300.4     .12       0
Bank Sta=275.4,300.4
XS Rating Curve= 0 ,0
Exp/Cntr=0.3,0.1

Type RM Length L Ch R = 1 ,5470.9  ,150.1,150.6,151.2
XS GIS Cut Line= 2
       1789211.2      202629.847      1789217.71      202122.034
#Sta/Elev= 30
       0 1440.98    48.8 1425.19    68.4 1419.28    78.1  1416.8   107.4  1411.1
   185.6 1394.37   195.3 1391.76   205.1 1388.53   214.9 1384.57   224.6 1381.15
   233.81379.592   244.2 1379.41   258.8 1379.42   273.5 1379.75   283.2 1380.96
   302.8 1383.76   312.5 1385.25   322.3 1387.12   341.8 1392.14   351.6 1392.86
   371.1  1392.7   380.9 1393.29   390.7 1395.04   400.4 1398.06   410.2 1402.05
   429.7 1411.86   439.5 1416.53   449.3 1420.91   498.1 1441.47   507.8 1445.33
#Mann= 3 ,-1 , 0
       0     .12       0   233.8    .045       0   258.8     .12       0
Bank Sta=233.8,258.8
XS Rating Curve= 0 ,0
Exp/Cntr=0.3,0.1

Type RM Length L Ch R = 1 ,5320.2  ,195.9,195.4,194.9
XS GIS Cut Line= 2
     1789347.919      202637.659      1789367.45      202142.867
#Sta/Elev= 30
       0 1440.99    38.8 1430.39   106.8  1413.1   135.9 1405.99   174.8 1397.02
   213.6 1387.78   223.3 1385.72     233 1383.99   242.7 1382.59   252.4 1381.39
   262.2  1380.3   271.9 1379.59  276.05 1379.52   291.3 1379.41     301  1379.5
   310.7 1380.32   320.4 1382.59   330.1  1386.1   339.8  1388.9   349.5 1391.45
   359.2 1393.19     369 1393.96   378.7 1394.28   388.4    1395   398.1 1396.85
   407.8    1400   427.2 1406.92   446.6  1413.6     466 1420.08   495.2 1429.64
#Mann= 3 ,-1 , 0
       0     .12       0  276.05    .045       0     301     .12       0
Bank Sta=276.05,301
XS Rating Curve= 0 ,0
Exp/Cntr=0.3,0.1