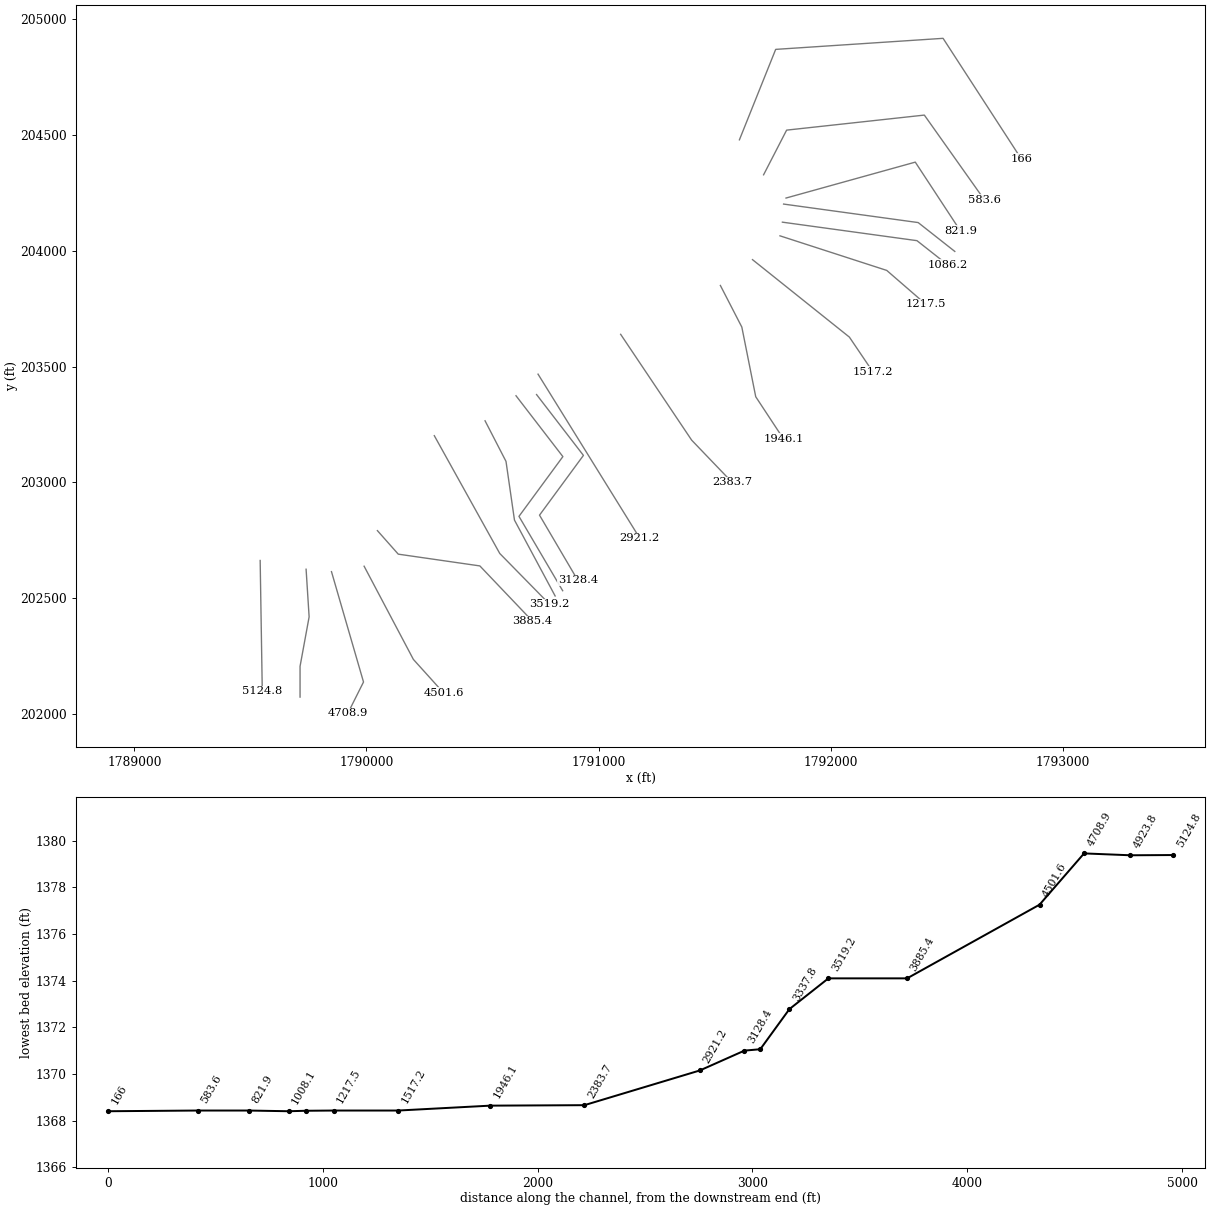
HEC-RAS study PECKSRN.prj: PECKSRN

--- PECKSRN.g01 (geometry) --- (continued)

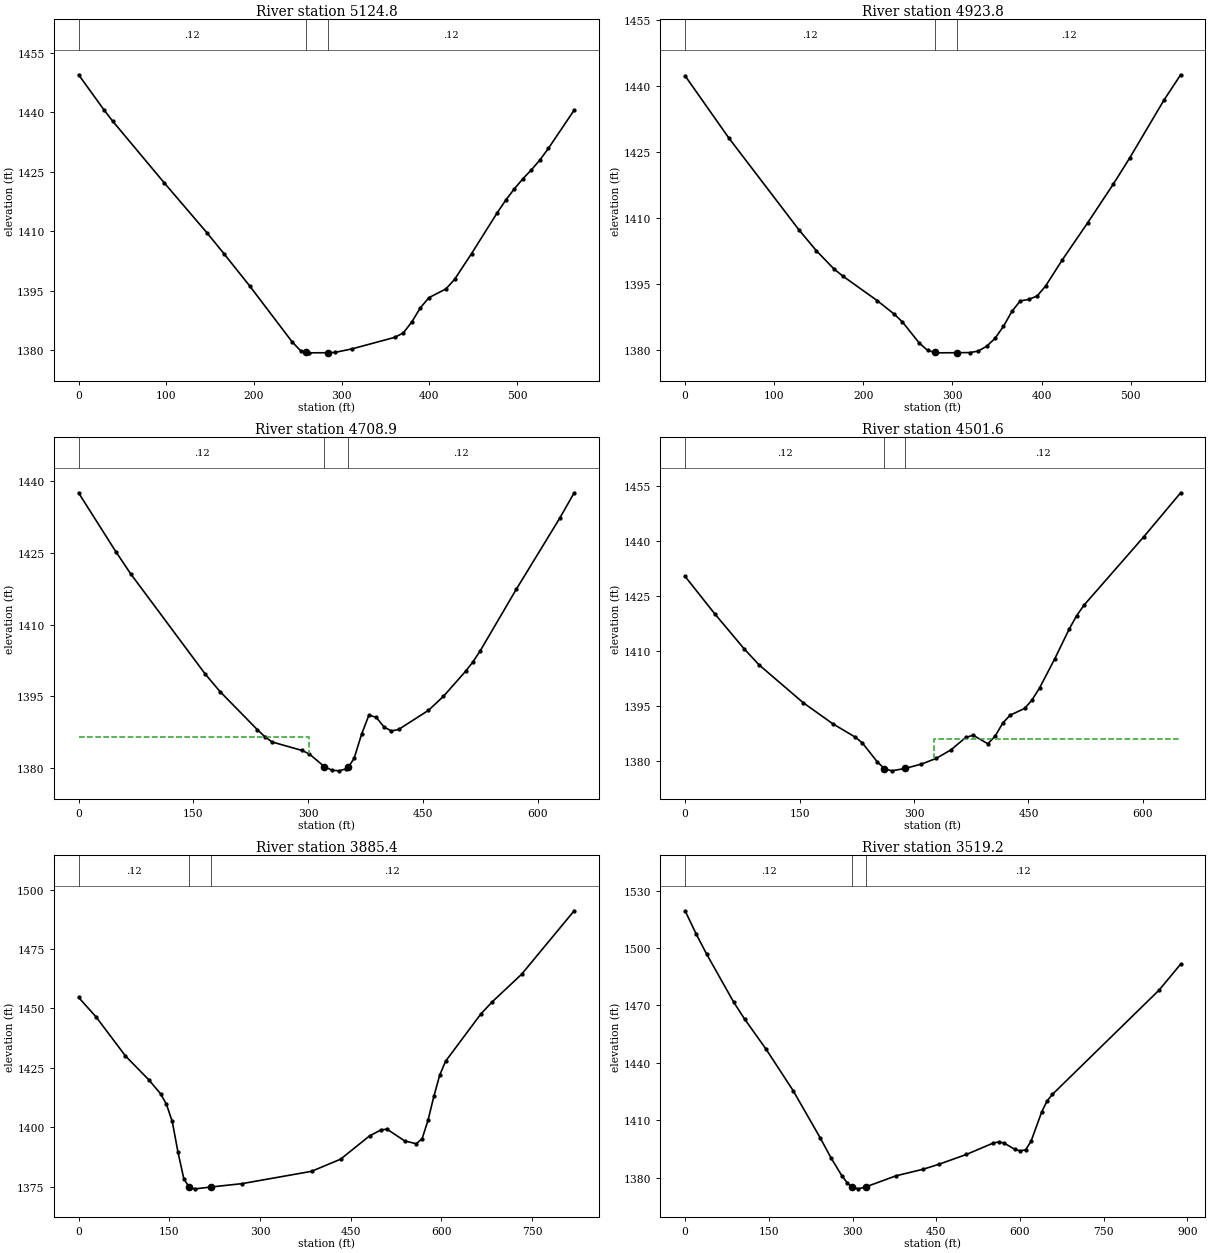
Type RM Length L Ch R = 1 ,5124.8  ,205.2,201,196.5
XS GIS Cut Line= 2
     1789541.929      202662.399     1789551.044      202097.295
#Sta/Elev= 30
       0 1449.42    29.2 1440.49      39  1437.7    97.4 1422.27   146.2 1409.67
   165.7 1404.38   194.9 1396.29   243.6 1382.13   253.4 1379.86   259.51379.564
   263.1 1379.39   284.51379.426   292.3 1379.49   311.8 1380.39   360.5 1383.29
   370.3  1384.4     380 1387.17   389.8 1390.74   399.5 1393.28     419  1395.5
   428.8 1397.89   448.2  1404.4   477.5 1414.69   487.2 1417.86     497 1420.71
   506.7 1423.23   516.5  1425.5   526.2 1427.98   535.9 1430.92   565.2 1440.52
#Mann= 3 ,-1 , 0
       0     .12       0   259.5    .045       0   284.5     .12       0
Bank Sta=259.5,284.5
XS Rating Curve= 0 ,0
Exp/Cntr=0.3,0.1

Type RM Length L Ch R = 1 ,4923.8  ,204.5,214.9,225.3
XS GIS Cut Line= 4
     1789739.846      202624.638     1789752.866      202418.909
     1789713.804      202205.367     1789713.804      202072.555
#Sta/Elev= 30
       0 1442.37    49.1 1428.22   127.6 1407.38   147.2 1402.61   166.9 1398.48
   176.7 1396.87   215.6 1391.25   234.5  1388.2   243.9  1386.4   262.8 1381.59
   272.2 1379.92   279.91379.478   281.6 1379.38   304.9 1379.41   319.4 1379.44
   328.8 1379.77   338.3 1380.87   347.7 1382.66   357.2 1385.41   366.6 1388.78
     376 1391.18   385.5 1391.53   394.9 1392.29   404.4 1394.55   423.2 1400.51
   451.7 1408.95   480.2 1417.66   499.1 1423.77   537.1 1436.78     556  1442.6
#Mann= 3 ,-1 , 0
       0     .12       0   279.9    .045       0   304.9     .12       0
Bank Sta=279.9,304.9
XS Rating Curve= 0 ,0
Exp/Cntr=0.3,0.1

Type RM Length L Ch R = 1 ,4708.9  ,202.6,207.3,212.1
XS GIS Cut Line= 3
     1789849.221      202614.222     1789987.241      202137.659
     1789919.533      202002.242
#Sta/Elev= 30
       0 1437.46    48.6 1425.21    68.1 1420.56   165.4 1399.67   184.8    1396
   233.5 1388.06   243.2  1386.6   252.9 1385.48   291.8 1383.72   301.6 1382.97
     321 1380.35   330.8 1379.61   340.5 1379.46     350 1379.91  352.39 1380.23
     360 1382.04   369.7 1387.07   379.4 1391.11   389.1  1390.6   398.9 1388.65
   408.6 1387.77   418.3 1388.11   457.2 1392.09   476.7    1395   505.6 1400.22
   515.1 1402.16   524.5 1404.42   571.8 1417.31   628.6 1432.15   647.6 1437.49
#Mann= 3 ,-1 , 0
       0     .12       0     321    .045       0  352.39     .12       0
#XS Ineff= 2 , 0
          300.52 1386.55
Permanent Ineff=
       F       F
Bank Sta=321,352.39
XS Rating Curve= 0 ,0
Exp/Cntr=0.3,0.1

Type RM Length L Ch R = 1 ,4501.6  ,592.2,616.2,638.8
XS GIS Cut Line= 3
     1789989.846      202637.659     1790202.085      202235.315
     1790332.294      202090.784
#Sta/Elev= 30
       0  1430.4    38.7 1420.22    77.4 1410.61    96.8 1406.25   154.9 1395.86
   193.6 1390.12   222.6 1386.52   232.3 1384.89   251.6 1379.78   261.3 1377.84
     271 1377.26  288.34 1377.92   309.7  1379.1   329.1 1380.66   348.4    1383
   367.8 1386.38   377.5 1386.99   396.8 1384.65   406.5  1386.8   416.2 1390.29
   425.9 1392.47   445.2 1394.34   454.9 1396.72   464.6 1399.94   484.1 1407.75
   503.5 1416.06   513.2  1419.7     523  1422.6   600.8 1441.16   649.4 1453.26
#Mann= 3 ,-1 , 0
       0     .12       0   261.3    .045       0  288.34     .12       0
#XS Ineff= 2 , 0
                           325.8         1386.01
Permanent Ineff=
       F       F
Bank Sta=261.3,288.34
XS Rating Curve= 0 ,0
Exp/Cntr=0.3,0.1

Type RM Length L Ch R = 1 ,3885.4  ,387,366.3,345.3
XS GIS Cut Line= 4
     1790047.137      202791.305     1790136.981      202689.742
     1790488.544      202638.961     1790715.106       202400.68
#Sta/Elev= 30
       0 1454.64    29.1 1446.37    77.5 1429.99   116.2 1419.95   135.6 1414.09
   145.2 1409.69   154.8 1402.47   164.4 1389.44     174  1378.3  182.22 1375.02
   183.4 1374.53   193.2  1374.1  218.22 1374.85     270 1376.28   385.2 1381.47
   433.2 1386.57   481.2 1396.38   500.5 1398.95   510.2 1399.18   539.2 1394.28
   558.5 1393.06   568.2 1395.27   577.8 1402.88   587.5 1412.99   597.2 1421.95
   606.9 1427.78   664.9 1447.58   684.2 1452.83   732.6 1464.38   819.6 1491.11
#Mann= 3 ,-1 , 0
       0     .12       0  182.22    .045       0  218.22     .12       0
Bank Sta=182.22,218.22
XS Rating Curve= 0 ,0
Exp/Cntr=0.3,0.1

Type RM Length L Ch R = 1 ,3519.2  ,189.5,181.4,173.1
XS GIS Cut Line= 3
     1790292.283      203201.324     1790574.358      202692.665
      1790788.66      202473.779
#Sta/Elev= 30
       0 1519.48    19.4  1507.6    38.8 1496.73    87.2 1471.65   106.6 1462.89
   145.4    1447   193.9 1425.29   242.4  1400.6   261.7 1390.18   281.1 1380.86
   290.8 1377.13  298.98 1375.12   310.2  1374.1  324.15 1375.15   378.1 1380.93
   426.5 1384.34   455.6 1387.02   504.1 1392.08   552.6 1398.09   562.2 1398.63
   571.9 1397.99   591.2 1394.69   600.8  1393.9   610.4 1394.59   619.9 1398.94
   639.1 1414.36   648.6 1420.04   658.2 1423.49   849.7  1478.1     888 1491.59
#Mann= 3 ,-1 , 0
       0     .12       0  298.98    .045       0  324.15     .12       0
Bank Sta=298.98,324.15
XS Rating Curve= 0 ,0
Exp/Cntr=0.3,0.1

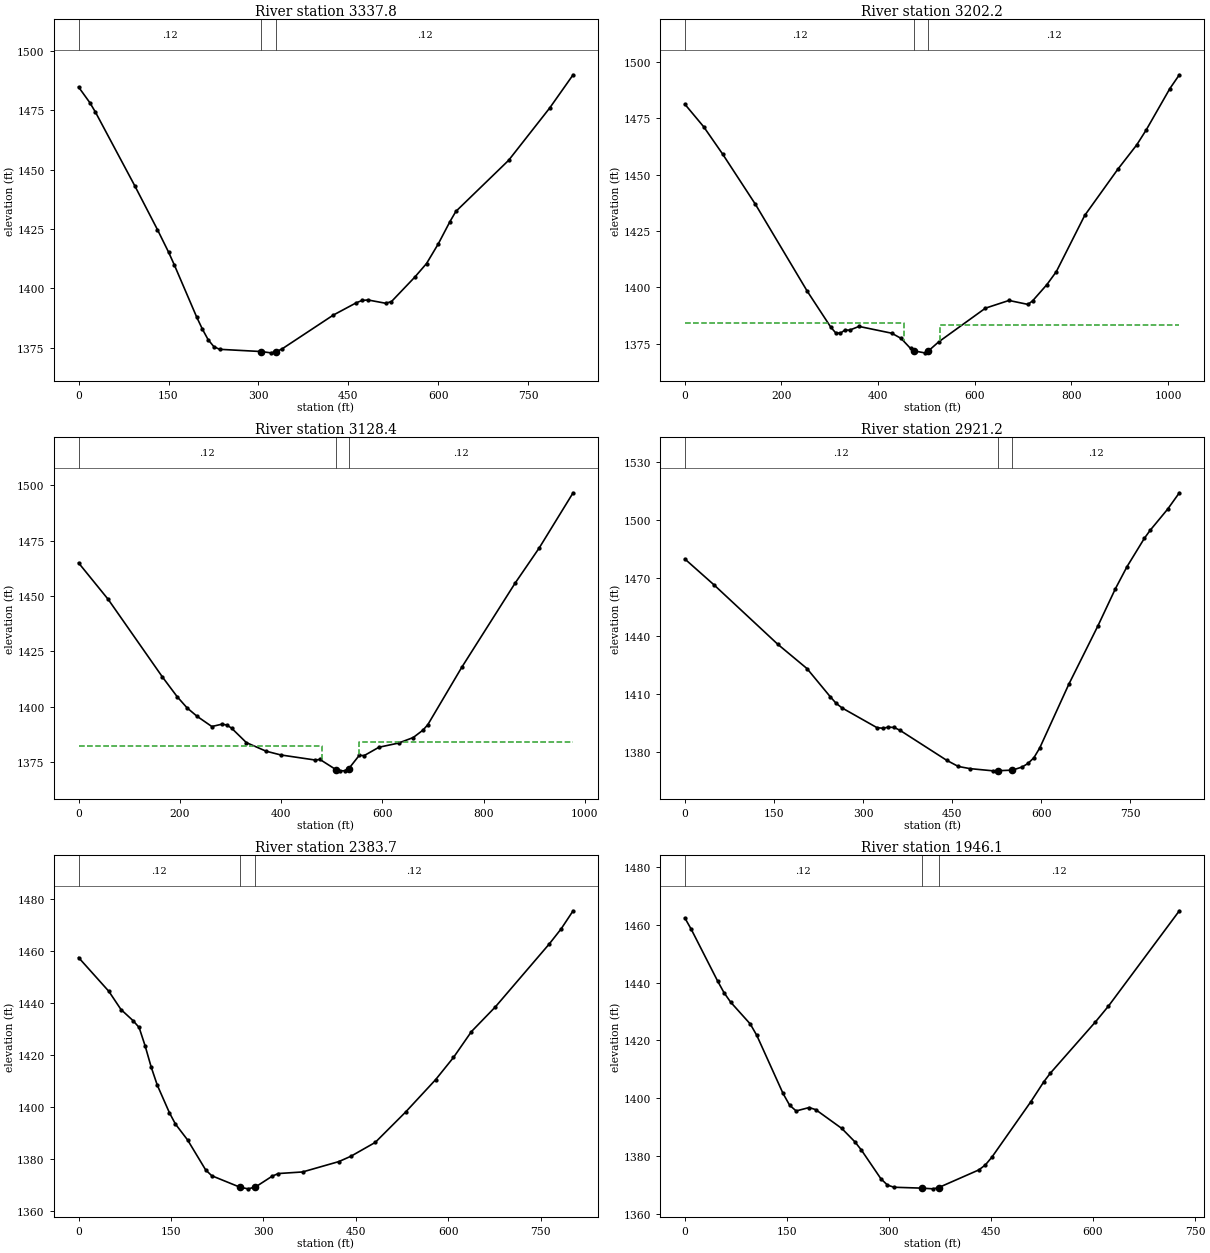
Type RM Length L Ch R = 1 ,3337.8  ,153.8,135.5,116.6
XS GIS Cut Line= 4
      1790510.99      203265.582     1790601.268      203090.234
     1790637.726      202836.762     1790813.008      202509.121
#Sta/Elev= 30
       0  1484.8    18.8 1478.21    28.2  1474.2    93.9  1443.1   131.5 1424.73
   150.3 1415.12   159.7 1409.83   197.2 1387.74   206.7 1382.69   216.2 1378.28
   225.7 1375.38   235.2 1374.27  305.04 1373.32   320.5 1372.78     330  1373.3
   339.5 1374.45   424.8 1388.68   463.1 1393.86   472.9 1394.86   482.6 1395.07
     512 1393.68   521.8 1394.36   560.9 1404.72   580.4 1410.42     600 1418.71
   619.5 1428.11   629.3 1432.38   717.3 1453.91   785.8 1475.96   824.9 1489.97
#Mann= 3 ,-1 , 0
       0     .12       0  305.04    .045       0     330     .12       0
Bank Sta=305.04,330
XS Rating Curve= 0 ,0
Exp/Cntr=0.3,0.1

Type RM Length L Ch R = 1 ,3202.2  ,74.3,73.8,74.3
XS GIS Cut Line= 4
     1790644.366      203373.676     1790846.315      203110.926
     1790657.112      202852.926     1790845.406      202531.901
#Sta/Elev= 30
       0  1481.2      39  1471.2      78 1459.18   146.2 1436.82   253.4 1398.35
   302.2  1382.4   311.9    1380   321.6 1379.71   331.4 1381.16   341.1 1381.12
   360.5 1382.76   428.3 1379.75   447.7 1377.44   467.1 1373.02  474.83  1371.9
   496.2 1371.06   504.21371.917   525.3  1375.9   622.2 1390.85   670.9 1394.26
   710.1 1392.51   719.9 1394.11   749.3 1401.26   768.9 1407.03   827.6  1431.9
   896.2 1452.39   935.4 1463.19     955 1469.81  1003.9 1488.11  1023.5 1494.21
#Mann= 3 ,-1 , 0
       0     .12       0  474.83    .045       0   504.2     .12       0
#XS Ineff= 2 , 0
          453.25 1384.36  528.79         1383.41
Permanent Ineff=
       F       F
Bank Sta=474.83,504.2
XS Rating Curve= 0 ,0
Exp/Cntr=0.3,0.1

Type RM Length L Ch R = 1 ,3128.4  ,178.8,207.2,234.5
XS GIS Cut Line= 4
     1790732.908      203378.884     1790934.857      203116.134
     1790745.654      202858.135     1790910.257      202577.499
#Sta/Elev= 30
       0 1464.94    58.5 1448.46   165.7 1413.37   194.9 1404.44   214.4 1399.42
   233.9 1395.66   263.2 1391.02   282.7 1392.06   292.4 1391.74   302.2 1390.28
   331.4 1383.75   370.2 1379.89   399.3 1378.18   467.1 1375.89   476.8 1376.13
   508.51371.518   515.6    1371   525.3 1371.04   533.51371.954   554.4 1378.01
   564.1 1377.89   593.2 1381.66   631.9 1383.54   660.9 1386.04     680 1389.36
   689.6  1391.8   756.6 1417.71   861.8 1455.68   909.7 1471.68   976.7 1496.62
#Mann= 3 ,-1 , 0
       0     .12       0   508.5    .045       0   533.5     .12       0
#XS Ineff= 2 , 0
          480.91 1382.23  554.18         1384.12
Permanent Ineff=
       F       F
Bank Sta=508.5,533.5
XS Rating Curve= 0 ,0
Exp/Cntr=0.3,0.1

Type RM Length L Ch R = 1 ,2921.2  ,537.2,537.5,538.2
XS GIS Cut Line= 2
     1790739.297      203466.996     1791177.455      202758.913
#Sta/Elev= 30
       0 1479.76      49  1466.4   156.7 1435.58   205.7 1423.06   244.9 1408.49
   254.7 1405.11   264.5 1402.74   323.3 1392.53   333.1 1392.17   342.9 1392.76
   352.7 1392.57   362.5 1391.08   440.8 1375.63   460.4 1372.43     480  1371.3
   519.2 1370.15   526.61370.203   551.61370.517   568.2 1372.16     578 1374.01
   587.8 1376.94   597.6 1381.97   646.6 1414.96   695.5 1445.09   724.9 1464.28
   744.5 1475.73   773.9 1490.49   783.7 1494.64   813.1 1505.56   832.7 1513.99
#Mann= 3 ,-1 , 0
       0     .12       0   526.6    .045       0   551.6     .12       0
Bank Sta=526.6,551.6
XS Rating Curve= 0 ,0
Exp/Cntr=0.3,0.1

Type RM Length L Ch R = 1 ,2383.7  ,446.2,437.6,428.8
XS GIS Cut Line= 3
     1791095.314      203638.961     1791401.304       203181.93
     1791575.783      202999.638
#Sta/Elev= 30
       0 1457.41    49.1 1444.45    68.8 1437.47    88.4  1433.2    98.2 1430.58
     108 1423.49   117.9 1415.31   127.7 1408.44   147.3  1397.9   157.1 1393.53
   176.8 1387.44   206.2 1375.91   216.1 1373.68   261.91369.279     275 1368.66
   286.91369.356   314.3 1373.55   324.1 1374.53   363.4 1375.14   422.3 1379.12
     442 1381.19   481.3 1386.48   530.4 1398.09   579.1 1410.52   608.2 1419.07
   637.4 1429.02   676.2 1438.49   763.5  1462.6   782.9 1468.43   802.3 1475.36
#Mann= 3 ,-1 , 0
       0     .12       0   261.9    .045       0   286.9     .12       0
Bank Sta=261.9,286.9
XS Rating Curve= 0 ,0
Exp/Cntr=0.3,0.1

Type RM Length L Ch R = 1 ,1946.1  ,413,428.9,444.8
XS GIS Cut Line= 4
     1791525.002      203849.899      1791617.45      203670.211
     1791677.346       203369.43     1791797.137      203187.138
#Sta/Elev= 30
       0 1462.36     9.6 1458.35    48.1 1440.57    57.7 1436.46    67.4 1433.21
    96.2 1425.66   105.8 1421.72   144.3 1401.67     154 1397.59   163.6 1395.58
   182.8 1396.76   192.4 1396.03   230.8 1389.52     250  1384.9   259.6 1382.04
   288.3  1372.1   297.9 1369.94   307.5 1369.19   348.11368.884     365 1368.64
   373.11369.079   432.1 1375.18   441.7 1376.89   451.3 1379.58   508.8 1398.84
   527.7 1405.68   537.2 1408.63   603.6 1426.39   622.6 1431.82   726.9 1464.82
#Mann= 3 ,-1 , 0
       0     .12       0   348.1    .045       0   373.1     .12       0
Bank Sta=348.1,373.1
XS Rating Curve= 0 ,0
Exp/Cntr=0.3,0.1

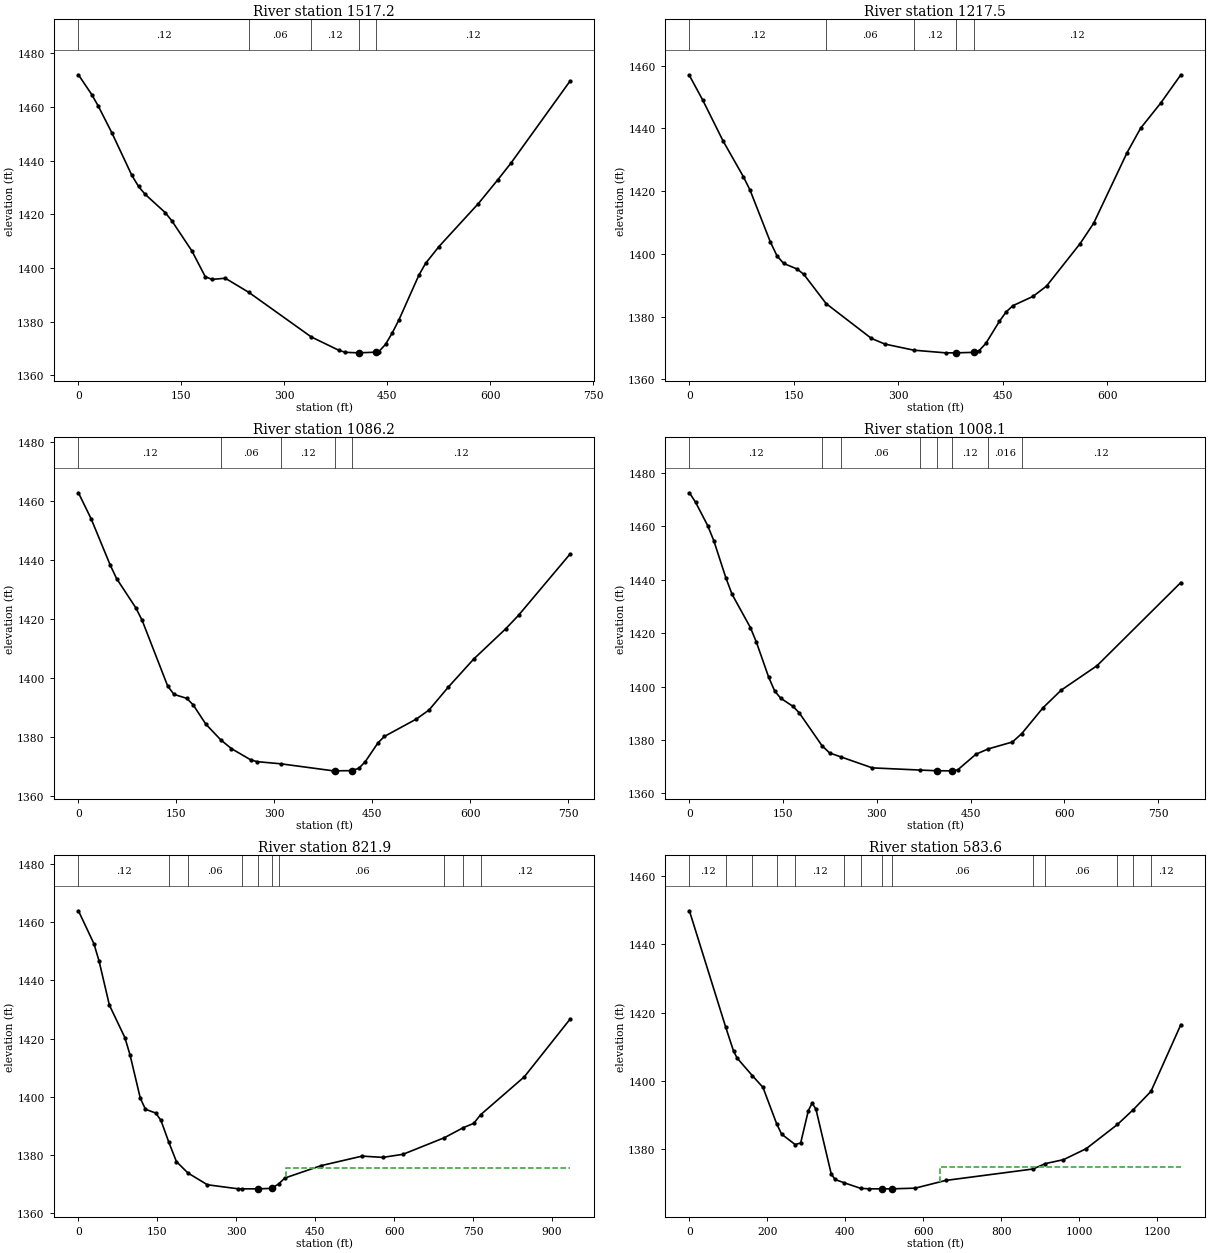
Type RM Length L Ch R = 1 ,1517.2  ,291.6,299.8,307.9
XS GIS Cut Line= 3
     1791663.379      203961.432     1792080.929      203626.919
      1792182.24      203476.785
#Sta/Elev= 30
       0    1472    19.5  1464.6    29.2  1460.2    48.6 1450.45    77.8 1434.56
    87.6  1430.4    97.3 1427.46   126.5 1420.66   136.2 1417.58   165.4 1406.36
   184.8  1396.8   194.6 1395.78     214 1396.22  248.341390.948  339.281374.353
   379.4 1369.39   389.1 1368.62   408.5 1368.43   433.51368.678   437.7 1368.87
   447.5 1371.61   457.2  1375.8   466.9 1380.65   496.1 1397.37   505.8 1401.74
   525.3 1408.01   582.7 1424.01   611.3 1432.96   630.4 1439.15   716.1 1469.57
#Mann= 5 ,-1 , 0
       0     .12       0  248.34     .06       0  339.28     .12       0
   408.5    .045       0   433.5     .12       0
Bank Sta=408.5,433.5
XS Rating Curve= 0 ,0
Exp/Cntr=0.3,0.1

Type RM Length L Ch R = 1 ,1217.5  ,127.2,131.2,135.2
XS GIS Cut Line= 3
     1791781.823      204064.193     1792241.893      203914.887
     1792409.346      203769.502
#Sta/Elev= 30
       0 1456.85    19.4 1448.89    48.4 1435.95    77.4 1424.61    87.1 1420.28
   116.1 1403.83   125.8 1399.32   135.4 1396.92   154.8 1395.13   164.4 1393.41
  196.29 1384.12   261.2 1373.04   280.5 1371.23  322.321369.272   367.6 1368.43
     383 1368.43     4081368.583     416 1369.16   425.6 1371.47     445 1378.49
   454.7 1381.49   464.3 1383.46   493.3 1386.43   512.6 1389.71   560.8 1403.25
   580.1 1409.68   628.3 1432.28   647.6 1440.02   676.5 1448.05   705.4 1457.07
#Mann= 5 ,-1 , 0
       0     .12       0  196.29     .06       0  322.32     .12       0
     383    .045       0     408     .12       0
Bank Sta=383,408
XS Rating Curve= 0 ,0
Exp/Cntr=0.3,0.1

Type RM Length L Ch R = 1 ,1086.2  ,78.1,78.2,78.1
XS GIS Cut Line= 3
      1791792.24       204123.22     1792372.101      204043.359
     1792503.074       203939.96
#Sta/Elev= 30
       0 1462.64    19.5  1453.8    48.8 1438.07    58.5 1433.54    87.8 1423.67
    97.6 1419.37   136.6 1397.16   146.3 1394.32   165.8 1392.98   175.6 1390.79
   195.1 1384.21  217.971378.893   234.1 1375.96   263.4 1372.18   273.2 1371.54
  309.651370.807   390.2 1368.42     3931368.424     4181368.488   429.2 1369.27
     439 1371.52   458.5  1377.9   468.3 1380.08     517 1385.94   536.6 1389.02
   565.8 1396.71     605  1406.3     654 1416.55   673.7 1421.15   752.2 1441.81
#Mann= 5 ,-1 , 0
       0     .12       0  217.97     .06       0  309.65     .12       0
     393    .045       0     418     .12       0
Bank Sta=393,418
XS Rating Curve= 0 ,0
Exp/Cntr=0.3,0.1

Type RM Length L Ch R = 1 ,1008.1  ,176.9,186.2,195.4
XS GIS Cut Line= 3
     1791797.448      204201.345     1792377.309      204121.484
      1792535.17      203996.858
#Sta/Elev= 30
       0 1472.64     9.8 1469.13    29.3 1460.32      39 1454.72    58.5 1440.67
    68.3 1434.58    97.6 1422.12   107.3 1416.59   126.8 1403.55   136.6 1398.27
   146.3 1395.59   165.8 1392.57   175.6 1390.19  212.331377.805   224.4  1375.1
  243.041373.581   292.7 1369.51  368.661368.698   395.9 1368.43   419.5  1368.4
   420.91368.448   429.2 1368.73   458.5 1374.61  477.811376.584     517 1379.22
  532.041382.395   565.8 1392.01   594.9 1398.63   652.4 1407.82   786.5    1439
#Mann= 8 ,-1 , 0
       0     .12       0  212.33    .016       0  243.04     .06       0
  368.66     .12       0   395.9    .045       0   420.9     .12       0
  477.81    .016       0  532.04     .12       0
Bank Sta=395.9,420.9
XS Rating Curve= 0 ,0
Exp/Cntr=0.3,0.1

Type RM Length L Ch R = 1 ,821.9   ,241.8,238.3,234.5
XS GIS Cut Line= 3
     1791807.865      204227.387     1792364.846      204382.451
     1792559.601      204085.026
#Sta/Elev= 30
       0 1463.84    29.4 1452.55    39.2 1446.61    58.8 1431.48    88.2 1420.34
      98 1414.42   117.6  1399.5   127.4 1395.73     147 1394.43   156.8  1391.9
  171.371384.605   186.2 1377.77  207.991373.878     245 1369.83   303.8 1368.43
  310.33 1368.43     342 1368.43     3671368.592  380.491370.119     392 1372.13
   460.6 1376.37     539 1379.66   578.2 1379.22   616.6 1380.28  695.431385.985
  731.131389.412   751.1  1390.9  764.021393.844   847.2 1406.88   933.7 1426.58
#Mann= 10 ,-1 , 0
       0     .12       0  171.37    .016       0  207.99     .06       0
  310.33     .12       0     342    .045       0     367     .12       0
  380.49     .06       0  695.43     .12       0  731.13    .016       0
  764.02     .12       0
#XS Ineff= 2 , 0
                          395.25         1375.61
Permanent Ineff=
       F       F
Bank Sta=342,367
XS Rating Curve= 0 ,0
Exp/Cntr=0.3,0.1

Type RM Length L Ch R = 1 ,583.6   ,419.2,417.6,415.1
XS GIS Cut Line= 4
       1791711.2      204327.763     1791810.425      204520.637
     1792403.908      204585.576     1792661.721      204220.992
#Sta/Elev= 30
       0 1449.86   92.921415.858   113.2 1408.78   122.6  1406.7  161.681401.546
   188.6 1398.16  223.611387.544   236.5 1384.45  271.151381.414   285.4 1381.85
     305  1391.3   314.8 1393.54   324.6 1391.74   363.7 1372.84   373.5 1371.17
  397.07  1370.2  439.091368.579   461.6 1368.43   493.6 1368.43   518.6 1368.43
     579 1368.63   657.3 1370.89   881.21374.237  912.781375.812   959.5 1376.97
  1017.8 1380.19 1097.981387.283 1138.911391.656 1183.831396.967  1260.5 1416.51
#Mann= 14 ,-1 , 0
       0     .12       0   92.92     .06       0  161.68     .12       0
  223.61    .016       0  271.15     .12       0  397.07     .06       0
  439.09     .12       0   493.6    .045       0   518.6     .06       0
   881.2     .08       0  912.78     .06       0 1097.98     .12       0
 1138.91    .016       0 1183.83     .12       0
#XS Ineff= 2 , 0
                          641.49         1374.86
Permanent Ineff=
       F       F
Bank Sta=493.6,518.6
XS Rating Curve= 0 ,0
Exp/Cntr=0.3,0.1

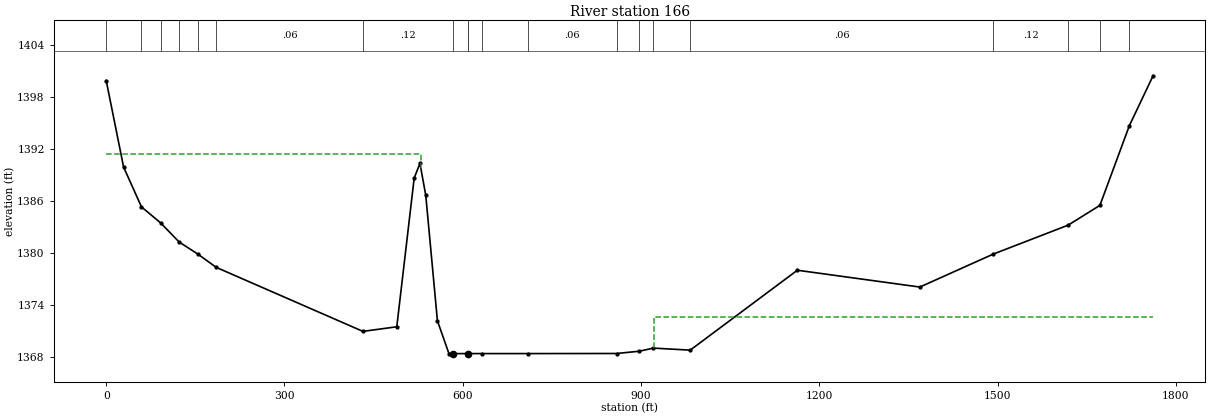
Type RM Length L Ch R = 1 ,166     ,170.3,166,161.5
XS GIS Cut Line= 4
     1791607.033      204478.805     1791763.292      204869.298
     1792484.592      204916.987     1792820.575      204398.076
#Sta/Elev= 30
       0 1399.91    29.3 1389.93   59.39 1385.34   91.611383.498   122.6  1381.3
  154.211379.903  185.15 1378.37     432 1370.99     489 1371.52   518.3 1388.67
     528 1390.36   537.8 1386.66   557.4 1372.21   576.9  1368.4     5841368.422
     609 1368.43  609.46 1368.43  632.49 1368.43  709.71 1368.43   858.91368.439
  896.961368.701  920.831369.061  982.761368.825  1163.1 1378.04  1369.2  1376.1
 1493.041379.909 1618.821383.238 1672.231385.519 1721.861394.717  1761.7 1400.46
#Mann= 20 ,-1 , 0
       0     .12       0   59.39     .06       0   91.61     .12       0
   122.6    .016       0  154.21     .12       0  185.15     .06       0
     432     .12       0     584    .045       0     609     .12       0
  609.46     .06       0  632.49     .12       0  709.71     .06       0
   858.9     .12       0  896.96     .06       0  920.83     .12       0
  982.76     .06       0 1493.04     .12       0 1618.82     .06       0
 1672.23     .12       0 1721.86     .06       0
#XS Ineff= 2 , 0
          530.44 1391.42   922.6         1372.64
Permanent Ineff=
       F       F
Bank Sta=584,609
XS Rating Curve= 0 ,0
Exp/Cntr=0.3,0.1

Chan Stop Cuts=-1
Use User Specified Reach Order=0
Composite Channel Slope=5